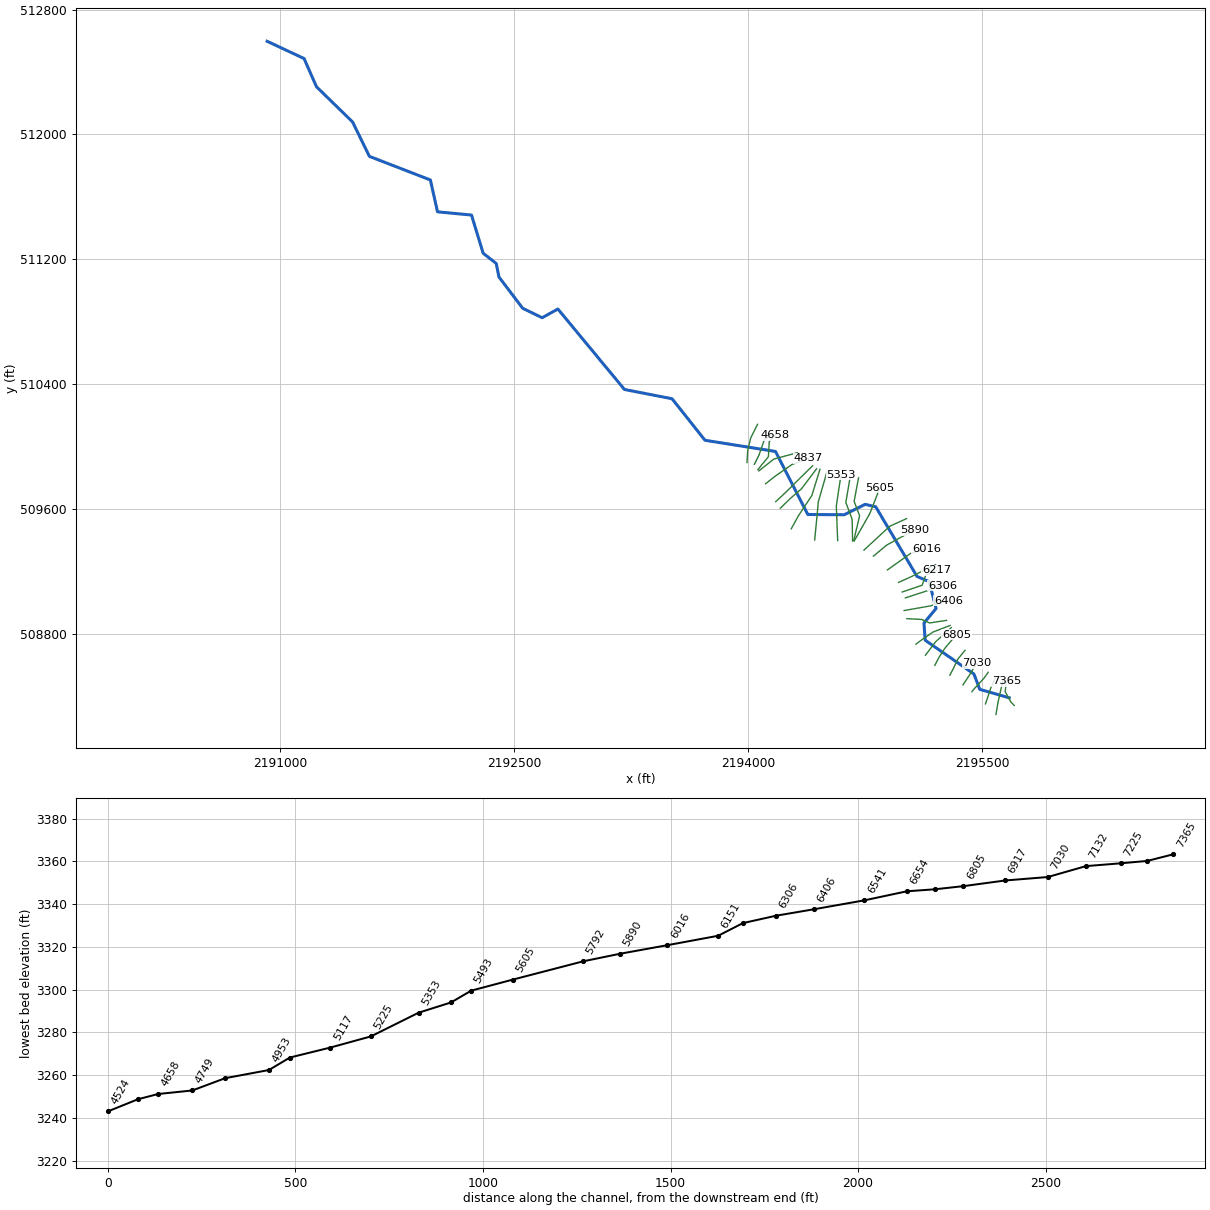
--- MFGAULYRV.prj (project) ---

Proj Title=MFGAULYRV
Current Plan=p01
Default Exp/Contr=0,0
English Units
Geom File=g01
Flow File=f01
Plan File=p01
Background Map Layer=Inundation Boundary (10pct Value_0)
BEGIN DESCRIPTION:
----------MODEL BY WOOD PLC 2021----------
Stream Name: Middle Fork Gauley River
Flood Zone: Approximate
Pocahontas County, WV
HEC-RAS Version: RAS 6.1
Vertical Datum: NAVD88
Projection: NAD 1983 StatePlane West Virginia S FIPS 4702 (US Feet)
Terrain: 1-meter LIDAR (FEMA Region III 3DEP collected 2016-2018)
Land Use: 2019 NLCD
Hydrologic Method:
WV 2010 Regional Regression Equations
Model Notes:
Model extends beyond county boundary on the downstream end
END DESCRIPTION:
DSS Export Rating Curves= 0
DSS Export Rating Curve Sorted= 0
DSS Export Volume Flow Curves= 0
DXF OffsetX= 0
DXF OffsetY= 0
DXF ScaleX= 0
DXF ScaleY= 0

--- MFGAULYRV.p01 (plan) ---

Plan Title=Floodplain
Program Version=6.10
Short Identifier=Floodplain
Geom File=g01
Flow File=f01
Subcritical Flow
K Sum by GR= 0
Std Step Tol= 0.01
Critical Tol= 0.01
Num of Std Step Trials= 20
Max Error Tol= 0.3
Flow Tol Ratio= 0.001
Split Flow NTrial= 30
Split Flow Tol= 0.02
Split Flow Ratio= 0.02
Log Output Level= 0
Friction Slope Method= 1
Unsteady Friction Slope Method= 2
Unsteady Bridges Friction Slope Method= 1
Parabolic Critical Depth
Global Vel Dist= 0 , 0 , 0
Global Log Level= 0
CheckData=True
Encroach Param=-1 ,0,0, 0
Mapping Interval=1HOUR
Computation Time Step Use Courant=        0
Computation Time Step Use Time Series=    0
Computation Time Step Count To Double=0
Computation Time Step Max Doubling=0
Computation Time Step Max Halving=0
Computation Time Step Residence Courant=0
Run HTab= 0
Run UNet= 0
Run Sediment= 0
Run PostProcess= 0
Run WQNet= 0
Run RASMapper=-1
UNET Theta= 0
UNET Theta Warmup= 0
UNET ZTol= 0
UNET ZSATol= 0
UNET MxIter= 0
UNET Max Iter WO Improvement= 0
UNET MaxInSteps= 0
UNET DtIC= 0
UNET DtMin= 0
UNET MaxCRTS= 0
UNET WFStab= 0
UNET SFStab= 0
UNET WFX= 1
UNET SFX= 1
UNET Gravity=32.174
UNET 1D Methodology=Finite Difference
UNET DSS MLevel= 1
UNET Pardiso=0
UNET DZMax Abort= 0
UNET Use Existing IB Tables= 0
UNET Froude Reduction=False
UNET Froude Limit= 0
UNET Froude Power= 0
UNET D1 Cores= 0
UNET WindReference=Eulerian
UNET WindDragFormulation=Hsu (1988)
UNET D2 Coriolis=0
UNET D2 Cores= 0
UNET D2 Theta= 1
UNET D2 Theta Warmup= 1
UNET D2 Z Tol= 0.01
UNET D2 Volume Tol= 0.01
UNET D2 Max Iterations= 20
UNET D2 Equation= 0
UNET D2 RampUpFraction=0.1
UNET D2 TimeSlices= 1
UNET D2 Turbulence Formulation=Non-Conservative (original)
UNET D2 Eddy Viscosity=0.3
UNET D2 Transverse Eddy Viscosity=0.1
UNET D2 Smagorinsky Mixing=0
UNET D2 BCVolumeCheck=0
UNET D2 Cores=0
UNET D2 SolverType=PARDISO (Direct)
UNET D2 Minimum Iterations= 2147483647
UNET D2 Maximum Iterations= 2147483647
UNET D2 Restart Number= 10
UNET D2 Relaxation Coeff=1.3
UNET D2 SOR Precondition Iterations= 10
UNET D2 ILUT Maximum Fill= 8
UNET D2 ILUT Tolerance=1E-08
UNET D1D2 MaxIter= 0
UNET D1D2 ZTol=0.01
UNET D1D2 QTol=0.1
UNET D1D2 MinQTol=1
Write IC File= 0
Write IC File at Fixed DateTime=0
Write IC File at Sim End=0
Echo Input=False
Echo Parameters=False
Echo Output=False
Write Detailed= 0
HDF Write Warmup=0
HDF Write Time Slices=0
HDF Flush=0
HDF Compression= 1
HDF Chunk Size= 1
HDF Spatial Parts= 1
HDF Use Max Rows=0
HDF Fixed Rows= 1
Calibration Method= 0
Calibration Iterations= 20
Calibration Max Change=0.05
Calibration Tolerance=0.2
Calibration Maximum=1.5
Calibration Minimum=0.5
Calibration Optimization Method= 1
WQ AD Non Conservative
WQ ULTIMATE=-1
WQ Max Comp Step=1HOUR
WQ Output Interval=15MIN
WQ Output Selected Increments= 0
WQ Output face flow=0
WQ Output face velocity=0
WQ Output face area=0
WQ Output face dispersion=0
WQ Output cell volume=0
WQ Output cell surface area=0
WQ Output cell continuity=0
WQ Output cumulative cell continuity=0
WQ Output face conc=0
WQ Output face dconc_dx=0
WQ Output face courant=0
WQ Output face peclet=0
WQ Output face adv mass=0
WQ Output face disp mass=0
WQ Output cell mass=0
WQ Output cell source sink temp=0
WQ Output nsm pathways=0
WQ Output nsm derived pathways=0
WQ Create Restart=0
WQ Fixed Restart=0
WQ System Summary=0
WQ Write To DSS=0
Sorting and Armoring Iterations= 10
XS Update Threshold= 0.02
Bed Roughness Predictor= 0
Hydraulics Update Threshold= 0.02
Energy Slope Method= 1
Volume Change Method= 1
Sediment Retention Method= 0
Sediment TS Multiplier= 1
Warm Up Method= 0
XS Weighting Method= 0
Number of US Weighted Cross Sections= 1
Number of DS Weighted Cross Sections= 1
Upstream XS Weight=0
Main XS Weight=1
Downstream XS Weight=0
Number of DS XS's Weighted with US Boundary= 1
Upstream Boundary Weight= 1
Weight of XSs Associated with US Boundary= 0
Number of US XS's Weighted with DS Boundary= 1
Downstream Boundary Weight= 0.5
Weight of XSs Associated with DS Boundary= 0.5
Percentile Method= 0
Sediment Output Level= 3
Mass or Volume Output= 0
Output Increment Type= 1
Profile and TS Output Increment= 1
Transport Output Increment 1
XS Output Flag= 0
XS Output Increment= 10
Read HDF5 Sediment Hotstart= 0
Sediment Hotstart Type= 0
Write Gradation File= 0
Read Gradation Hotstart= 0
Write HDF5 File= 1
Write Binary Output= 1
Write DSS Sediment File= 0
DSS Sediment Output Type= 1
SV Curve= 0
Specific Gage Flag= 0
Subcell Erosion Methods= 0
Subcell Deposition Methods= 0
Advection Scheme= 1
Matrix Solver= 0
Implicit Weighting Factor= 1
Maximum Outer Loop Convergence Iterations= 5
Convergence Maximum Absolute= 0.001
Convergence RMSE= 0.0001
Grain Fractions Max Abs Error= 0.001
Max Subgrid Regions= 1
Max Subgrid Length Scale= 3.402823E+38
Initial Layer Thickness= 3.402823E+38
Min Layer Thickness= 3.402823E+38
Max Layer Thickness= 3.402823E+38
Number of Layers= 5

--- MFGAULYRV.f01 (steady flow) ---

Flow Title=Flow
Program Version=6.10
Number of Profiles= 6
Profile Names=01pct,10pct,04pct,02pct,0_2pct,01plus
River Rch & RM=MFGAULYRV,Main            ,7365
     671     357     473     569     934     992
River Rch & RM=MFGAULYRV,Main            ,2350
     781     417     552     663    1080    1150
River Rch & RM=MFGAULYRV,Main            ,785
     849     455     600     720    1180    1250
Boundary for River Rch & Prof#=MFGAULYRV,Main            , 1
Up Type= 0
Dn Type= 1
Dn Known WS=3059.9
Boundary for River Rch & Prof#=MFGAULYRV,Main            , 2
Up Type= 0
Dn Type= 1
Dn Known WS=3059
Boundary for River Rch & Prof#=MFGAULYRV,Main            , 3
Up Type= 0
Dn Type= 1
Dn Known WS=3059.4
Boundary for River Rch & Prof#=MFGAULYRV,Main            , 4
Up Type= 0
Dn Type= 1
Dn Known WS=3059.7
Boundary for River Rch & Prof#=MFGAULYRV,Main            , 5
Up Type= 0
Dn Type= 1
Dn Known WS=3069.3
Boundary for River Rch & Prof#=MFGAULYRV,Main            , 6
Up Type= 0
Dn Type= 1
Dn Known WS=3060.6
DSS Import GetInterval= 0
DSS Import GetPeak= 0
DSS Import FillOption= 0

--- MFGAULYRV.g01 (geometry) ---

Geom Title=Geometry
Program Version=6.10

River Reach=MFGAULYRV       ,Main
Reach XY= 30
     2195673.117      508391.224     2195484.183      508445.513
     2195446.696      508543.879     2195134.148      508760.369
     2195126.636      508870.425     2195204.335       508963.54
     2195159.504      509135.342     2195082.045      509168.792
     2194817.323      509614.961     2194749.574      509630.496
     2194615.474      509563.928     2194382.236      509565.507
     2194175.169      509969.355     2193723.171      510041.041
     2193512.109      510307.053     2193207.002      510366.485
     2192780.643      510881.831     2192679.758      510826.109
     2192554.974      510886.527     2192402.771       511086.89
     2192385.534      511173.439     2192301.637      511239.091
     2192226.979      511483.859     2192009.079      511504.442
     2191963.548      511708.406     2191572.756      511859.664
     2191464.637      512080.312     2191233.353      512305.656
     2191153.893      512486.386     2190917.181      512596.959

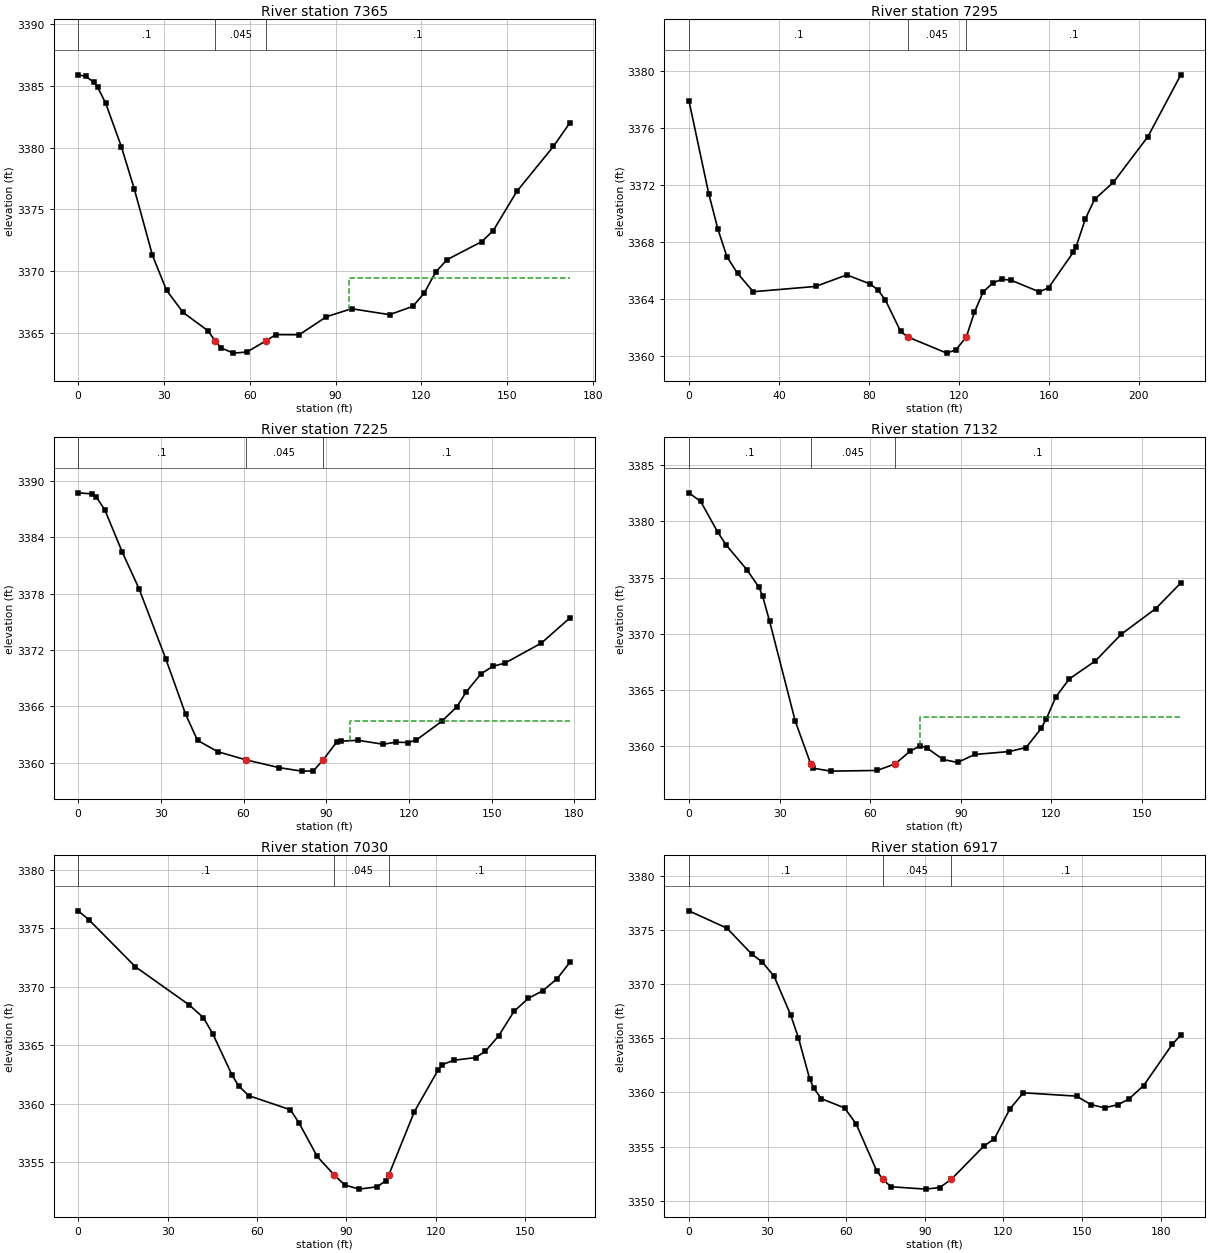
Type RM Length L Ch R = 1 ,7365    ,80.1,69.9,60.1
XS GIS Cut Line= 4
2195704.81549023508342.1506234982195683.06528193508365.418288189
 2195647.1521473508430.1630942852195653.72779167508495.919537977
#Sta/Elev= 30
       0 3385.91     2.6 3385.79     5.4 3385.33     6.8 3384.91     9.6 3383.63
    15.1 3380.09    19.6 3376.68      26 3371.26    30.9 3368.44    36.7 3366.64
    45.3 3365.17   47.883364.356    49.9 3363.77    54.3 3363.34      59 3363.43
   65.833364.357    69.1 3364.84    77.3 3364.83    86.8 3366.29    95.6 3366.94
   108.9 3366.46     117 3367.13     121  3368.2     125 3369.91     129 3370.92
   141.1 3372.38   145.1 3373.26   153.4 3376.46   166.2 3380.11     172 3382.04
#Mann= 3 ,-1,0
       0      .1       0   47.88    .045       0   65.83      .1       0
#XS Ineff= 1 ,-1
   94.65171.9731 3369.41
Permanent Ineff=
       F
Bank Sta=47.88,65.83
XS Rating Curve= 0 ,0
Exp/Cntr(USF)=0,0
Exp/Cntr=0.3,0.1

Type RM Length L Ch R = 1 ,7295    ,71.7,70,68.7
XS GIS Cut Line= 4
2195587.97134798508284.4872805682195601.12263672  508362.8891942
2195615.79138185508428.1398190952195632.48340217508498.448631965
#Sta/Elev= 30
       0 3377.94     8.8 3371.42    12.9 3368.91    16.9 3366.99    21.6 3365.82
    28.6 3364.53    56.3  3364.9    70.2 3365.71    80.6 3365.07      84 3364.65
    87.3 3363.95    94.1 3361.74    97.33361.353   114.6 3360.22   118.7 3360.46
  123.283361.354   126.9  3363.1   130.8 3364.52   135.1 3365.15   139.2 3365.41
   143.3 3365.33   155.7 3364.52   159.8  3364.8   170.8  3367.3   172.1  3367.7
   176.2 3369.65   180.3 3371.02   188.6  3372.2     204 3375.42   218.6 3379.75
#Mann= 3 ,-1,0
       0      .1       0    97.3    .045       0  123.28      .1       0
Bank Sta=97.3,123.28
XS Rating Curve= 0 ,0
Exp/Cntr(USF)=0,0
Exp/Cntr=0.3,0.1

Type RM Length L Ch R = 1 ,7225    ,100.5,93.6,84.3
XS GIS Cut Line= 4
 2195520.6974479 508352.266999452195535.36619303508394.755778451
2195553.06985094508449.384208595 2195584.4306164 508518.68138387
#Sta/Elev= 30
       0 3388.72     5.2  3388.6     6.6 3388.28     9.7 3386.89      16 3382.42
    22.1 3378.51    31.8 3371.05      39 3365.15    43.3 3362.39    50.7 3361.18
   60.743360.329    72.9 3359.49    81.1 3359.12    85.3 3359.14   88.893360.329
    93.7 3362.19    95.2  3362.3   101.5  3362.4   110.6 3361.98   115.3  3362.2
   119.7 3362.16   122.7 3362.44   131.8  3364.4   137.3 3365.95   140.8 3367.56
   146.1 3369.47   150.4 3370.27   154.8 3370.61     168 3372.74   178.4 3375.43
#Mann= 3 ,-1,0
       0      .1       0   60.74    .045       0   88.89      .1       0
#XS Ineff= 2 , 0
                           98.57         3364.44
Permanent Ineff=
       F       F
Bank Sta=60.74,88.89
XS Rating Curve= 0 ,0
Exp/Cntr(USF)=0,0
Exp/Cntr=0.3,0.1

Type RM Length L Ch R = 1 ,7132    ,96.1,101.4,97.8
XS GIS Cut Line= 4
 2195433.6966147508430.1630942852195449.88281623 508450.39584619
2195510.07525314508515.6464710842195538.40110581508554.594518502
#Sta/Elev= 30
       0 3382.53     3.9 3381.76     9.6 3379.01    12.4 3377.87    19.2 3375.69
    23.2 3374.13    24.4 3373.34    26.7 3371.12    35.2 3362.23   40.313358.433
    41.1 3358.05      47 3357.79    62.3 3357.85   68.263358.434    73.2 3359.56
    76.5 3360.04    78.7 3359.86    84.1 3358.83    88.9 3358.56    94.6 3359.27
     106 3359.53   111.6 3359.89   116.6 3361.59   118.3 3362.45   121.5 3364.41
   125.9 3365.99   134.5 3367.58   143.1 3369.96   154.5 3372.24   162.8 3374.52
#Mann= 3 ,-1,0
       0      .1       0   40.31    .045       0   68.26      .1       0
#XS Ineff= 2 , 0
                           76.63         3362.64
Permanent Ineff=
       F       F
Bank Sta=40.31,68.26
XS Rating Curve= 0 ,0
Exp/Cntr(USF)=0,0
Exp/Cntr=0.3,0.1

Type RM Length L Ch R = 1 ,7030    ,112.1,113.7,115.8
XS GIS Cut Line= 4
2195376.53909057508474.1693296792195415.48713799508532.844310204
2195445.33044705508582.4145523712195466.06901775508612.763680229
#Sta/Elev= 30
       0 3376.47     3.6 3375.71    19.2 3371.69    37.2 3368.44      42 3367.35
    45.2 3365.94    51.6 3362.45    53.8 3361.52    57.2 3360.68    71.2 3359.47
    74.1 3358.34    80.2 3355.48   85.933353.883    89.5 3353.04    94.2 3352.69
   100.3 3352.89   103.2 3353.41  104.173353.884   112.8 3359.32   120.7 3362.85
   122.2 3363.33     126  3363.7   133.3 3363.93   136.5 3364.45     141 3365.77
   146.2 3367.88     151 3368.99   155.9 3369.65   160.7 3370.68     165 3372.09
#Mann= 3 ,-1,0
       0      .1       0   85.93    .045       0  104.17      .1       0
Bank Sta=85.93,104.17
XS Rating Curve= 0 ,0
Exp/Cntr(USF)=0,0
Exp/Cntr=0.3,0.1

Type RM Length L Ch R = 1 ,6917    ,113.6,111.5,109.2
XS GIS Cut Line= 4
2195292.57317016508536.3850417872195312.80592207508574.827270407
2195344.16668752508640.0778953012195389.69037931 508695.71796304
#Sta/Elev= 30
       0 3376.78    14.5 3375.18      24 3372.78      28 3372.05    32.5 3370.74
    38.8 3367.18    41.8 3365.04    46.1 3361.24    47.7 3360.38    50.5 3359.43
    59.4 3358.57    63.8  3357.1    71.7 3352.74   74.063351.963    77.1 3351.29
    90.4 3351.07    95.7 3351.22  100.083351.964   112.6 3355.06   116.6 3355.73
   122.4 3358.45   127.6 3359.97   147.9 3359.66   153.4 3358.88   158.6 3358.58
   163.8 3358.88   167.8 3359.38   173.5 3360.63   184.4 3364.44   187.7 3365.31
#Mann= 3 ,-1,0
       0      .1       0   74.06    .045       0  100.08      .1       0
Bank Sta=74.06,100.08
XS Rating Curve= 0 ,0
Exp/Cntr(USF)=0,0
Exp/Cntr=0.3,0.1

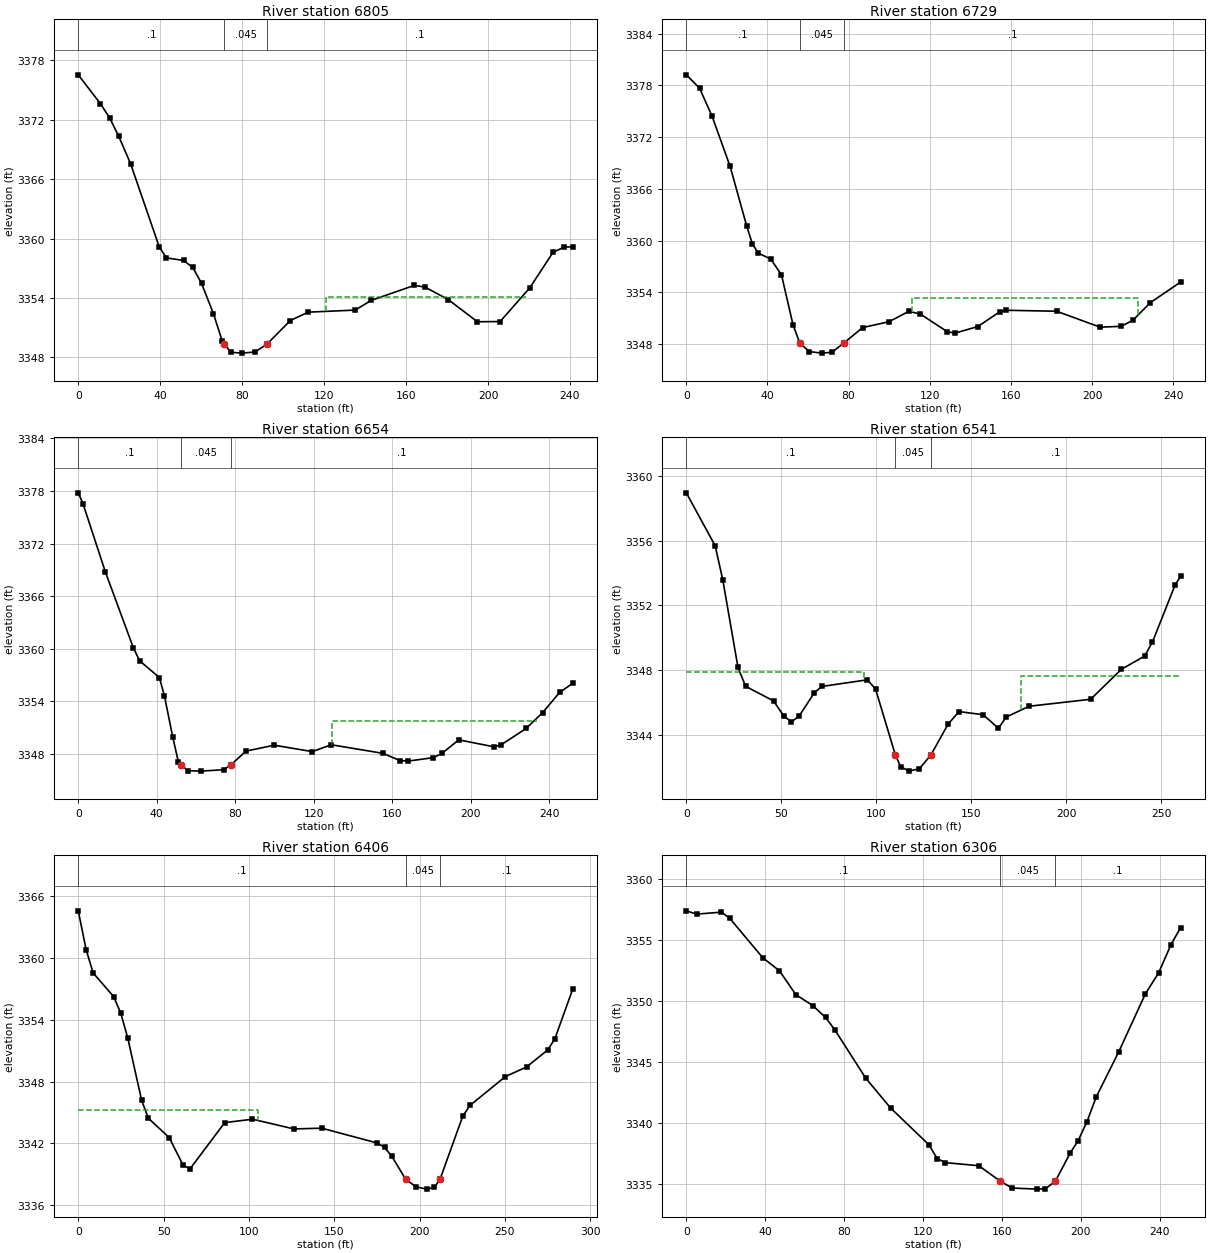
Type RM Length L Ch R = 1 ,6805    ,77.2,76,74.9
XS GIS Cut Line= 4
2195196.46759862508599.612391491 2195221.2527197508647.665177265
2195261.21240471508709.3750705762195334.62753224508796.191419035
#Sta/Elev= 30
       0 3376.54    10.8 3373.63    15.3  3372.2    19.8 3370.31    25.5 3367.58
    39.5 3359.17      43 3358.05    51.4 3357.78    55.9 3357.08    60.2 3355.46
      66 3352.39    70.2 3349.68   71.253349.302    74.6 3348.51    79.7 3348.42
    86.2 3348.53   91.983349.303   103.5 3351.71   112.2 3352.56   135.2 3352.77
     143 3353.75     164 3355.26   169.2  3355.1   180.6 3353.83   194.8 3351.59
   205.9 3351.61   220.4 3355.02   231.7  3358.6   237.3 3359.15   241.3 3359.15
#Mann= 3 ,-1,0
       0      .1       0   71.25    .045       0   91.98      .1       0
#XS Ineff= 1 ,-1
  120.74 218.715 3354.12
Permanent Ineff=
       F
Bank Sta=71.25,91.98
XS Rating Curve= 0 ,0
Exp/Cntr(USF)=0,0
Exp/Cntr=0.3,0.1

Type RM Length L Ch R = 1 ,6729    ,80,74.7,69.8
XS GIS Cut Line= 4
2195135.65485716508663.9755784672195161.32741617 508697.97437282
2195201.57088703508750.7071967162195301.69660176508840.972591419
#Sta/Elev= 30
       0 3379.23     6.5 3377.69    12.7 3374.43    21.6  3368.6    29.8 3361.66
    32.6  3359.6    35.5 3358.55    41.6 3357.86    46.9 3356.04    52.6 3350.23
   55.893348.154    60.5 3347.13    66.8 3346.95    71.8 3347.05   77.813348.154
    86.9 3349.91     100  3350.6   109.7  3351.8   115.4 3351.48   128.6 3349.44
   132.4 3349.27   143.7 3350.03   154.4 3351.73   157.8 3351.92   182.5 3351.81
     204 3349.96   214.5 3350.06   220.2 3350.78   228.7  3352.8   243.7  3355.2
#Mann= 3 ,-1,0
       0      .1       0   55.89    .045       0   77.81      .1       0
#XS Ineff= 1 ,-1
  111.11222.5112 3353.33
Permanent Ineff=
       F
Bank Sta=55.89,77.81
XS Rating Curve= 0 ,0
Exp/Cntr(USF)=0,0
Exp/Cntr=0.3,0.1

Type RM Length L Ch R = 1 ,6654    ,129.2,113.2,95.7
XS GIS Cut Line= 4
2195075.28965086508734.7485789582195107.20688638508759.033432068
2195184.22456338508812.4601089092195294.31893595508854.817394477
#Sta/Elev= 30
       0 3377.79     2.4 3376.56    13.8 3368.76    28.1 3360.07    31.3  3358.6
    41.3  3356.7    43.9 3354.59    48.1 3349.93      51 3347.05   52.493346.693
    55.9 3346.06    62.5 3346.01      74 3346.17   77.543346.695    85.5  3348.3
    99.8 3348.97   119.2 3348.24   128.9 3349.02   155.2 3348.04   163.8 3347.22
   168.1 3347.16   180.9 3347.55   185.2 3348.03   193.8 3349.58   211.7 3348.79
   215.2 3348.99   228.1 3350.88   236.5 3352.69   245.2    3355   251.8 3356.03
#Mann= 3 ,-1,0
       0      .1       0   52.49    .045       0   77.54      .1       0
#XS Ineff= 1 ,-1
  128.99233.7283 3351.68
Permanent Ineff=
       F
Bank Sta=52.49,77.54
XS Rating Curve= 0 ,0
Exp/Cntr(USF)=0,0
Exp/Cntr=0.3,0.1

Type RM Length L Ch R = 1 ,6541    ,121.3,135.2,143.2
XS GIS Cut Line= 4
 2195017.0060034508898.4978742122195113.45156289508892.947050644
2195162.71512206508870.7437563732195270.95618163508887.396227077
#Sta/Elev= 30
       0 3358.94    15.2 3355.67    19.2 3353.57    27.2 3348.17    31.2 3347.01
    45.9 3346.11    51.3 3345.18    55.3 3344.82    59.3 3345.16    67.3  3346.6
    71.3    3347    95.3 3347.41    99.6 3346.84  110.023342.776   112.8 3342.06
   117.1 3341.78   122.7 3341.93  128.723342.776   137.8 3344.68   143.5 3345.45
   156.2 3345.26   164.3 3344.42   168.3 3345.11   180.4 3345.78   212.8 3346.21
     229 3348.06   241.2 3348.87   245.3 3349.73   257.3 3353.27   260.2  3353.8
#Mann= 3 ,-1,0
       0      .1       0  110.02    .045       0  128.72      .1       0
#XS Ineff= 2 ,-1
       0    93.4 3347.88  176.29260.1556 3347.65
Permanent Ineff=
       F       F
Bank Sta=110.02,128.72
XS Rating Curve= 0 ,0
Exp/Cntr(USF)=0,0
Exp/Cntr=0.3,0.1

Type RM Length L Ch R = 1 ,6406    ,99.2,100.2,101
XS GIS Cut Line= 4
2194999.65016188 508950.420727112195167.16472771508979.926133593
2195231.88626451508998.9618797112195282.33099173509012.286901993
#Sta/Elev= 30
       0 3364.53     4.6 3360.78     8.7 3358.52    20.8 3356.21    24.9 3354.63
      29 3352.22    37.1  3346.2    41.1 3344.44    53.3 3342.57    61.5 3339.88
    65.5 3339.54    85.8 3344.02   102.1 3344.35   126.4 3343.41   142.7 3343.48
   175.3 3342.04   179.5 3341.62   183.7 3340.77  191.793338.555   197.7 3337.82
   204.1 3337.58   208.7 3337.75  212.053338.555   225.3 3344.64   229.5 3345.68
   250.3 3348.48   262.7 3349.41   275.1 3351.06   279.2 3352.11   289.7 3356.92
#Mann= 3 ,-1,0
       0      .1       0  191.79    .045       0  212.05      .1       0
#XS Ineff= 2 , 0
          105.61 3345.23
Permanent Ineff=
       F       F
Bank Sta=191.79,212.05
XS Rating Curve= 0 ,0
Exp/Cntr(USF)=0,0
Exp/Cntr=0.3,0.1

Type RM Length L Ch R = 1 ,6306    ,74.2,88.4,101.5
XS GIS Cut Line= 4
2195007.26446032509031.322648111 2195132.9003847509072.249502264
2195208.09158187509097.947759523 2195245.2112868  509110.3209945
#Sta/Elev= 30
       0  3357.4     5.2 3357.13    17.8 3357.29      22 3356.79    38.8 3353.55
    47.2 3352.49    55.6 3350.52    64.1 3349.64    70.6 3348.66    75.2 3347.67
      91 3343.68   103.7 3341.22     123 3338.23   127.2  3337.1   131.4 3336.76
   148.3 3336.51  159.21 3335.24   165.2 3334.68   177.9 3334.59   182.1 3334.62
  187.153335.241   194.8 3337.59   198.5  3338.5   203.2 3340.13   207.9 3342.16
   219.3 3345.85   232.8  3350.6   239.5 3352.31   245.8 3354.64   250.7 3356.03
#Mann= 3 ,-1,0
       0      .1       0  159.21    .045       0  187.15      .1       0
Bank Sta=159.21,187.15
XS Rating Curve= 0 ,0
Exp/Cntr(USF)=0,0
Exp/Cntr=0.3,0.1

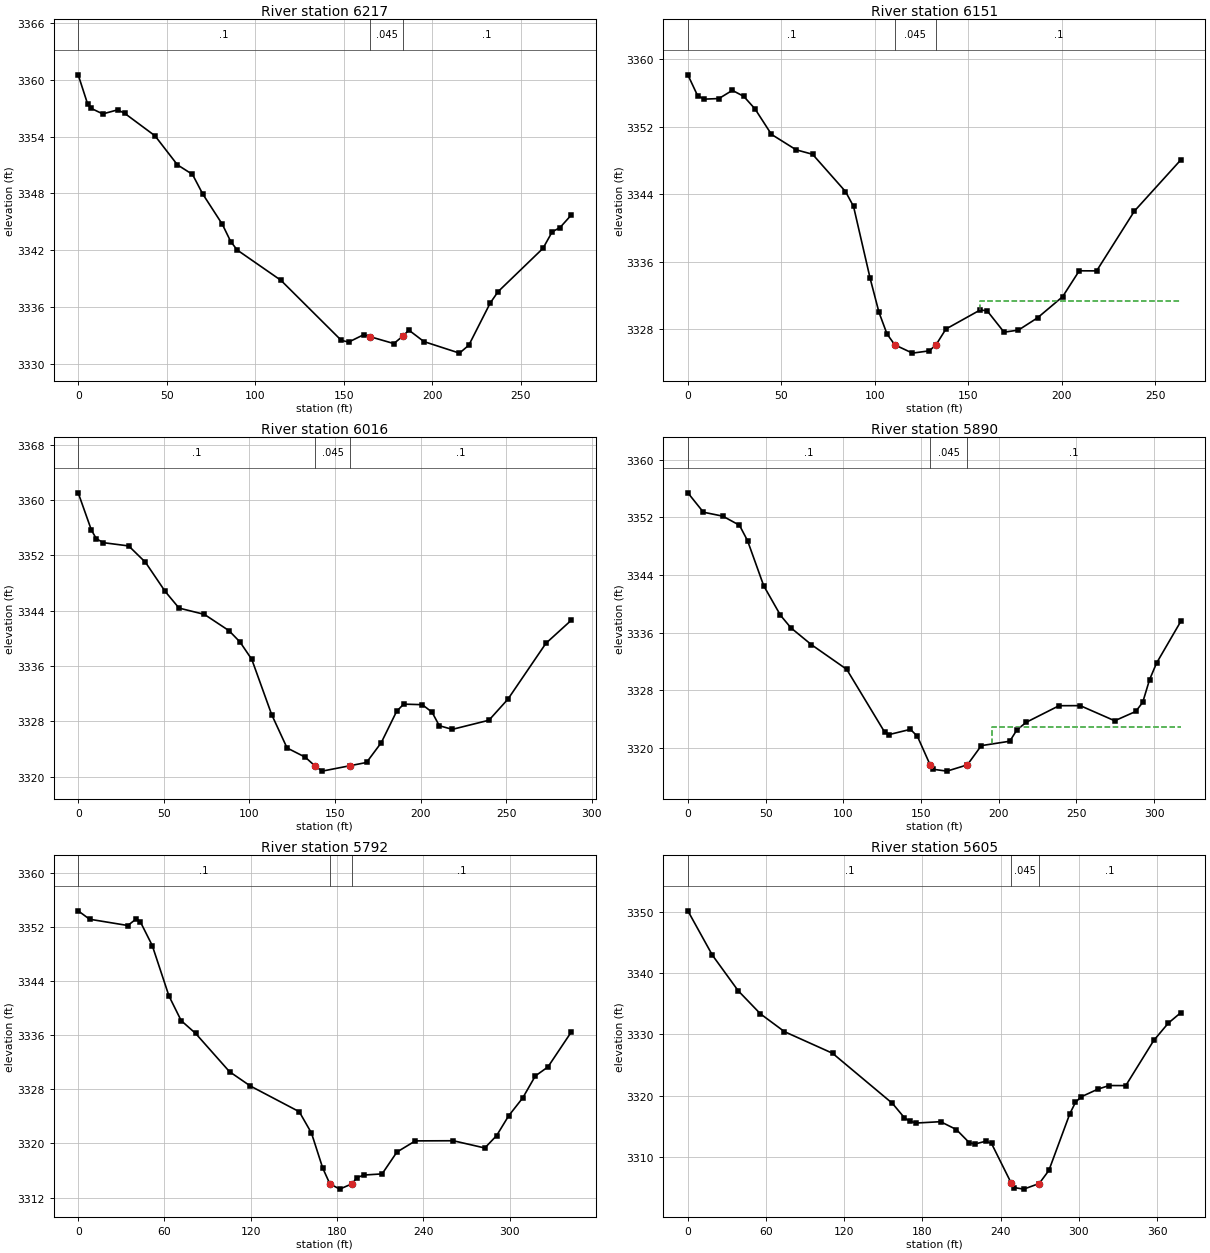
Type RM Length L Ch R = 1 ,6217    ,77.8,66.1,53.8
XS GIS Cut Line= 4
 2194987.0245739509069.0128672092195114.98708947509112.372066699
2195138.25300139509177.9396366612195205.93565425509207.550797288
#Sta/Elev= 30
       0 3360.53     5.4 3357.41     7.3 3356.99    13.9  3356.4    22.3 3356.83
    26.3 3356.46    43.4 3354.09    56.1 3351.02    64.6 3350.01    70.4 3347.94
    81.5 3344.73    86.2 3342.92    89.9 3342.02   114.6 3338.82   148.7 3332.48
   152.9  3332.3   161.4 3333.08   164.9 3332.87   178.4 3332.14   183.7 3332.96
   186.9 3333.56   195.4 3332.35   215.5 3331.13   220.8 3331.97   232.9 3336.43
   237.3 3337.62   262.7  3342.2   267.9 3343.94   272.3 3344.39   278.6  3345.7
#Mann= 3 ,-1,0
       0      .1       0   164.9    .045       0   183.7      .1       0
Bank Sta=164.9,183.7
XS Rating Curve= 0 ,0
Exp/Cntr(USF)=0,0
Exp/Cntr=0.3,0.1

Type RM Length L Ch R = 1 ,6151    ,132.3,135.2,137.7
XS GIS Cut Line= 4
2194963.48224425509130.3085279242195047.23952717509168.380020159
2195151.93613082509220.7283219832195201.42907072509243.571217324
#Sta/Elev= 30
       0 3358.16     5.2  3355.7     8.7 3355.28    16.6 3355.35    23.8 3356.32
    29.9 3355.61    35.9 3354.13    44.7 3351.11    57.9 3349.28    66.7 3348.75
    84.3 3344.34    88.6 3342.58    97.5 3334.04   102.2 3330.04   106.5 3327.47
  110.683326.179   120.1  3325.2   129.1 3325.47   132.7 3326.18     138 3328.05
   156.4 3330.32   160.1  3330.2   169.1 3327.68   176.8 3327.93     187 3329.38
   200.4 3331.88   209.3 3334.95   218.6 3334.94   238.8 3342.02   263.6 3348.08
#Mann= 3 ,-1,0
       0      .1       0  110.68    .045       0   132.7      .1       0
#XS Ineff= 1 ,-1
  156.44263.5684 3331.42
Permanent Ineff=
       F
Bank Sta=110.68,132.7
XS Rating Curve= 0 ,0
Exp/Cntr(USF)=0,0
Exp/Cntr=0.3,0.1

Type RM Length L Ch R = 1 ,6016    ,128.8,126.5,125
XS GIS Cut Line= 3
  2194892.174965509210.3763415092195040.76893776509316.219181044
2195142.41825776509344.460671749
#Sta/Elev= 30
       0 3361.05     7.7 3355.67    10.6 3354.41    14.7 3353.84    29.5 3353.37
    39.3    3351    50.8 3346.79    58.9 3344.38    73.7 3343.47    88.1 3341.11
    94.5 3339.48   101.4 3336.96     113 3328.98     122 3324.15   132.6 3322.82
138.44713321.518   142.5  3320.8   158.7 3321.58   168.4 3322.05     177 3324.91
     186 3329.45   190.1 3330.49     201 3330.41   206.7 3329.32   210.9 3327.37
   218.5 3326.84   239.9 3328.16     251 3331.21   273.2 3339.29   287.9  3342.6
#Mann= 3 ,-1,0
       0      .1       0138.4471    .045       0   158.7      .1       0
Bank Sta=138.4471,158.7
XS Rating Curve= 0 ,0
Exp/Cntr(USF)=0,0
Exp/Cntr=0.3,0.1

Type RM Length L Ch R = 1 ,5890    ,91.3,98,99
XS GIS Cut Line= 4
2194802.63018956509298.7748810662194887.33925978509369.207141702
 2194987.2769269509424.4108054432195070.08242251509466.289446903
#Sta/Elev= 30
       0 3355.41      10 3352.72    22.5 3352.17    33.2 3350.91    38.4 3348.77
    48.8 3342.51    59.6 3338.41    66.3 3336.67    79.5 3334.33   102.2 3330.91
   126.7 3322.16   129.4 3321.85   143.2 3322.58   147.7  3321.6  155.86 3317.65
   157.9 3317.03   166.7 3316.78   179.83317.648   188.8 3320.32   207.1 3320.93
   211.7 3322.51   217.7 3323.56   238.8 3325.86   252.4 3325.87   274.6 3323.77
   288.1 3325.06   292.6 3326.32     297 3329.46   301.5 3331.77   317.1 3337.56
#Mann= 3 ,-1,0
       0      .1       0  155.86    .045       0   179.8      .1       0
#XS Ineff= 2 , 0
                          195.98         3322.88
Permanent Ineff=
       F       F
Bank Sta=155.86,179.8
XS Rating Curve= 0 ,0
Exp/Cntr(USF)=0,0
Exp/Cntr=0.3,0.1

Type RM Length L Ch R = 1 ,5792    ,178.7,187,190.1
XS GIS Cut Line= 3
2194742.37844326509337.7777050082194907.51871493509490.411659914
2195014.82244568509539.108876749
#Sta/Elev= 30
       0 3354.38     7.9 3353.14    34.5 3352.21    40.5 3353.21    43.3 3352.72
    51.5 3349.25    63.1  3341.8    71.6 3338.15    81.6 3336.27   105.2 3330.61
   119.7 3328.49   153.7 3324.69   162.2 3321.53     170 3316.37  174.95 3314.04
   181.8 3313.25   190.5 3314.05   193.6 3314.92   198.5 3315.33   211.3  3315.5
   221.6 3318.73   234.4 3320.38   260.8  3320.4   282.7 3319.33   290.9 3321.16
   299.3 3324.09   309.1 3326.74   317.8 3329.97   326.6 3331.31   342.7 3336.43
#Mann= 3 ,-1,0
       0      .1       0  174.95    .045       0   190.5      .1       0
Bank Sta=174.95,190.5
XS Rating Curve= 0 ,0
Exp/Cntr(USF)=0,0
Exp/Cntr=0.3,0.1

Type RM Length L Ch R = 1 ,5605    ,101.6,111.6,122.9
XS GIS Cut Line= 4
 2194679.8496271509396.8089735732194779.78729422509571.937837856
2194818.81057376509671.8755049752194843.55704371509736.597041775
#Sta/Elev= 30
       0 3350.15    18.8 3342.92    38.6 3337.11    55.7 3333.33    74.1 3330.43
     111  3326.9     157 3318.71   166.2 3316.36   170.1 3315.82   175.4 3315.51
   193.9 3315.73     206 3314.45   215.9 3312.31   220.1 3312.07   228.7 3312.55
     233 3312.17  248.273305.639   250.2 3304.98   257.7 3304.72  269.593305.638
     277 3307.77   293.1 3317.04   297.4 3318.88   301.7 3319.78   314.6 3321.04
   323.2 3321.63     336 3321.62   357.5    3329   368.7 3331.83   378.2 3333.52
#Mann= 3 ,-1,0
       0      .1       0  248.27    .045       0  269.59      .1       0
Bank Sta=248.27,269.59
XS Rating Curve= 0 ,0
Exp/Cntr(USF)=0,0
Exp/Cntr=0.3,0.1

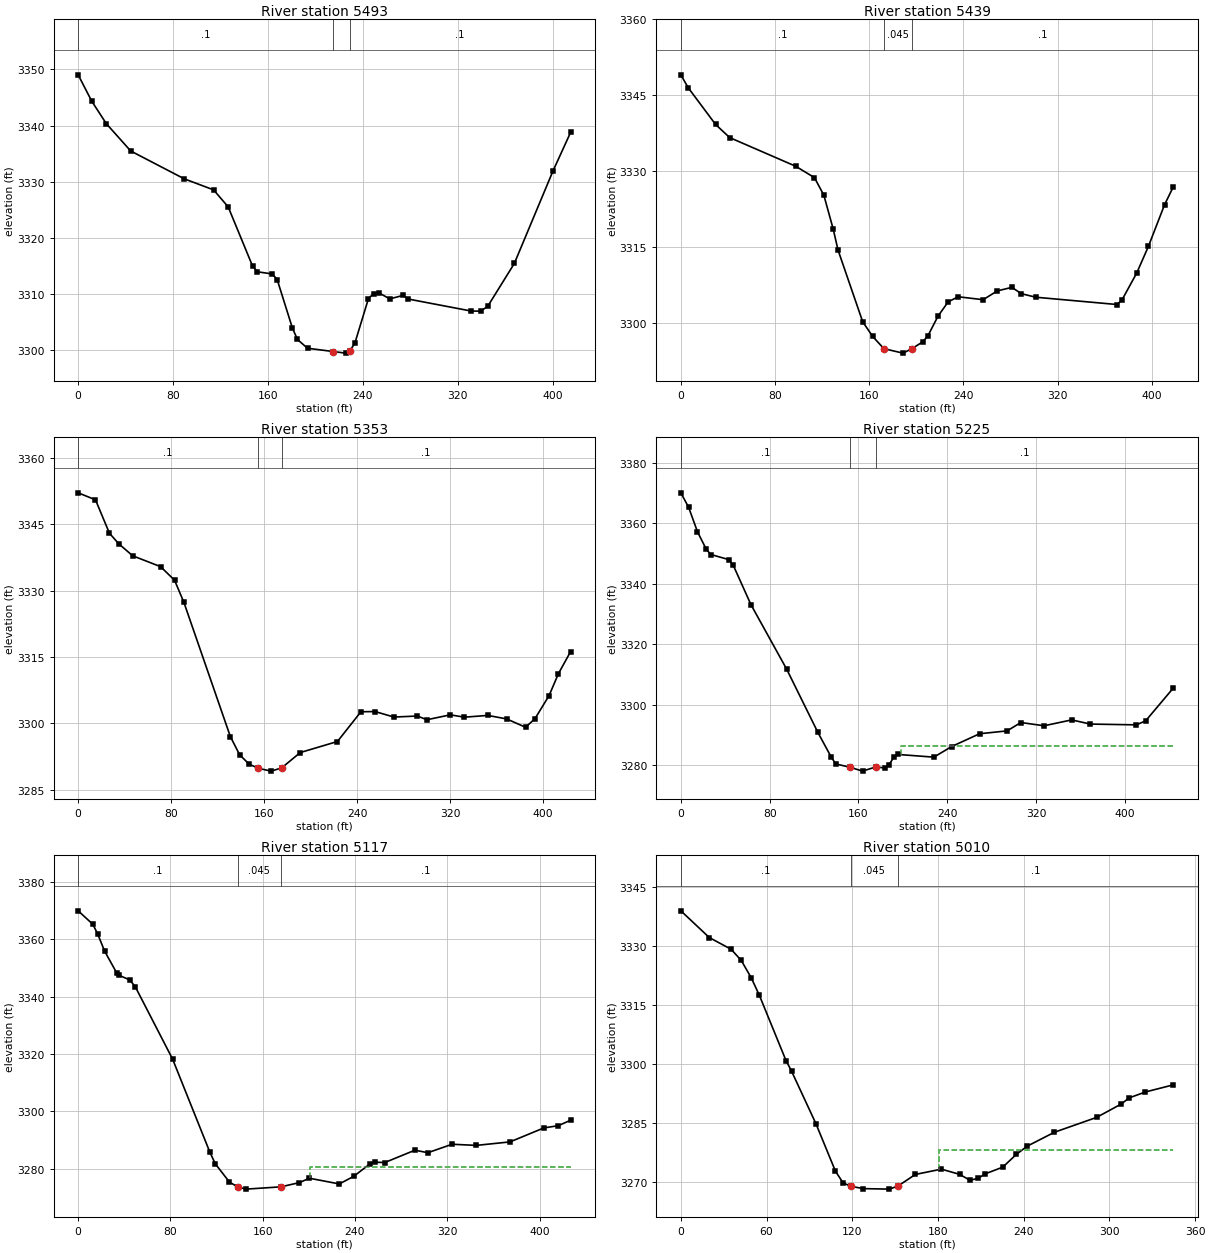
Type RM Length L Ch R = 1 ,5493    ,57.6,54.1,54
XS GIS Cut Line= 4
2194676.41500616509398.0714494582194714.10578348509557.400644464
2194678.98483189509649.9143705972194707.25291487509799.820871275
#Sta/Elev= 30
       0 3349.04    11.4 3344.37    23.7 3340.36    44.3 3335.49    89.5 3330.53
   114.2 3328.57   126.5 3325.54   147.1 3314.99   151.2 3313.99   163.7 3313.61
   167.8 3312.62   180.6 3304.02   184.9 3301.95   193.4 3300.39   215.2  3299.8
   225.5 3299.52     229 3299.91   233.3 3301.28   244.8 3309.24   249.1  3310.1
   253.3 3310.29   262.7 3309.17   274.1  3309.8   278.2 3309.15   331.1 3307.02
   339.3 3306.98   345.3 3307.83   367.8 3315.48   400.3 3331.89   415.2 3338.78
#Mann= 3 ,-1,0
       0      .1       0   215.2    .045       0     229      .1       0
Bank Sta=215.2,229
XS Rating Curve= 0 ,0
Exp/Cntr(USF)=0,0
Exp/Cntr=0.3,0.1

Type RM Length L Ch R = 1 ,5439    ,91.2,86.1,80.6
XS GIS Cut Line= 4
2194669.01570246509395.722708774  2194666.404489509534.117022113
2194625.93068038509642.482380671 2194653.3484217509804.377615143
#Sta/Elev= 30
       0 3349.04     6.2  3346.5    29.5 3339.22    41.5 3336.62    97.5 3330.96
   113.5  3328.7   121.5 3325.21   129.5 3318.46   133.5 3314.39   154.5 3300.17
     163 3297.27  172.483294.862   188.7 3293.98  196.263294.862   205.7 3296.24
     210 3297.46   218.5 3301.31   227.1 3304.13   235.6 3305.13   256.8 3304.55
   268.8 3306.29   281.2 3306.99   289.3 3305.74   301.5 3305.04   370.4  3303.6
   374.5  3304.4   387.3 3309.84   397.2  3315.1   410.9 3323.33   418.3 3326.86
#Mann= 3 ,-1,0
       0      .1       0  172.48    .045       0  196.26      .1       0
Bank Sta=172.48,196.26
XS Rating Curve= 0 ,0
Exp/Cntr(USF)=0,0
Exp/Cntr=0.3,0.1

Type RM Length L Ch R = 1 ,5353    ,129.7,127.3,125
XS GIS Cut Line= 3
2194573.49507819509398.3339222332194564.86902135509620.373928423
2194594.67532759509819.497759037
#Sta/Elev= 30
       0 3352.15    14.9 3350.57    26.9 3343.01    34.9 3340.63    46.9 3337.91
    70.9 3335.45    82.9 3332.39    90.9 3327.41   130.9 3297.02   138.9  3292.9
     147  3290.8154.83193289.865   165.9 3289.21     175 3289.93     191 3293.41
     223 3295.91   243.2 3302.64   255.4 3302.68   271.6 3301.44   291.8 3301.67
   299.9 3300.83   320.1 3301.94   332.2 3301.41   352.4 3301.81   368.6 3301.01
   384.8 3299.13   392.9 3301.07     405 3306.28   413.1 3311.27   423.5 3316.22
#Mann= 3 ,-1,0
       0      .1       0154.8319    .045       0     175      .1       0
Bank Sta=154.8319,175
XS Rating Curve= 0 ,0
Exp/Cntr(USF)=0,0
Exp/Cntr=0.3,0.1

Type RM Length L Ch R = 1 ,5225    ,115.5,108.3,99.1
XS GIS Cut Line= 4
2194426.17285075509402.2507424222194437.92331131509522.366561547
2194449.67377188 509647.704807592194504.50925452509837.017783384
#Sta/Elev= 30
       0 3370.13       7 3365.35      15 3357.23      23  3351.4    27.1 3349.73
    43.1 3348.06    47.2 3346.19    63.2 3333.13    95.4 3311.79   123.5 3290.89
   135.6 3282.69   139.6 3280.48  152.413279.402   163.7 3278.11   175.7  3279.5
   183.8 3279.15   187.8 3280.28   191.8 3282.71   195.8 3283.62     228 3282.73
     244 3286.24   269.2 3290.47   293.9 3291.41   306.4 3294.18   327.3 3293.11
   352.2 3295.05   368.9 3293.67   410.5 3293.41   418.9 3294.76   443.7 3305.56
#Mann= 3 ,-1,0
       0      .1       0  152.41    .045       0   175.7      .1       0
#XS Ineff= 1 ,-1
  198.02443.6718 3286.55
Permanent Ineff=
       F
Bank Sta=152.41,175.7
XS Rating Curve= 0 ,0
Exp/Cntr(USF)=0,0
Exp/Cntr=0.3,0.1

Type RM Length L Ch R = 1 ,5117    ,109.8,107.5,96.5
XS GIS Cut Line= 4
2194276.02807684509474.0591125512194323.02991911509558.923549976
2194407.89435653509686.8730094782194460.11862572509855.296277598
#Sta/Elev= 30
       0 3369.93    12.7 3365.25    16.8 3361.97      23 3355.82    33.3 3348.36
    35.6 3347.43    44.7 3345.84    49.5 3343.47    81.9  3318.2   114.1 3285.85
   118.9  3281.7   131.2 3275.32  138.233273.674   145.6 3272.88  175.713273.675
   191.8 3275.15   200.5 3276.68   226.4 3274.69   238.9 3277.33     253  3281.7
   257.1 3282.27   265.8 3282.15     292 3286.46   303.2 3285.58   324.2 3288.53
   345.1 3288.13   374.4 3289.35   403.7 3294.22   416.3 3295.01   426.9  3296.9
#Mann= 3 ,-1,0
       0      .1       0  138.23    .045       0  175.71      .1       0
#XS Ineff= 1 ,-1
  201.32426.8805 3280.55
Permanent Ineff=
       F
Bank Sta=138.23,175.71
XS Rating Curve= 0 ,0
Exp/Cntr(USF)=0,0
Exp/Cntr=0.3,0.1

Type RM Length L Ch R = 1 ,5010    ,56.2,56.1,54.9
XS GIS Cut Line= 4
2194205.92655333509605.7152129332194267.67946552509666.080419235
2194341.92173074509730.6087432132194438.36729024509858.277685276
#Sta/Elev= 30
       0 3338.99    19.9  3332.2    35.2 3329.21    42.3 3326.37    49.3 3321.94
      55 3317.48    73.6 3300.93    77.6 3298.14    94.6 3284.84   108.2 3272.81
   113.5 3269.85   118.8 3268.97   127.7 3268.36     146 3268.23   152.1 3269.04
   164.2 3271.97   182.4 3273.31   195.1 3271.99   202.4 3270.49     208 3270.96
     213 3272.11   225.3 3273.81   234.9 3277.07   242.4 3279.14   261.5 3282.69
     291 3286.46   308.3 3289.87   313.8 3291.42   325.2 3292.93   344.7 3294.74
#Mann= 3 ,-1,0
       0      .1       0   118.8    .045       0   152.1      .1       0
#XS Ineff= 2 , 0
                          181.01         3278.08
Permanent Ineff=
       F       F
Bank Sta=118.8,152.1
XS Rating Curve= 0 ,0
Exp/Cntr(USF)=0,0
Exp/Cntr=0.3,0.1

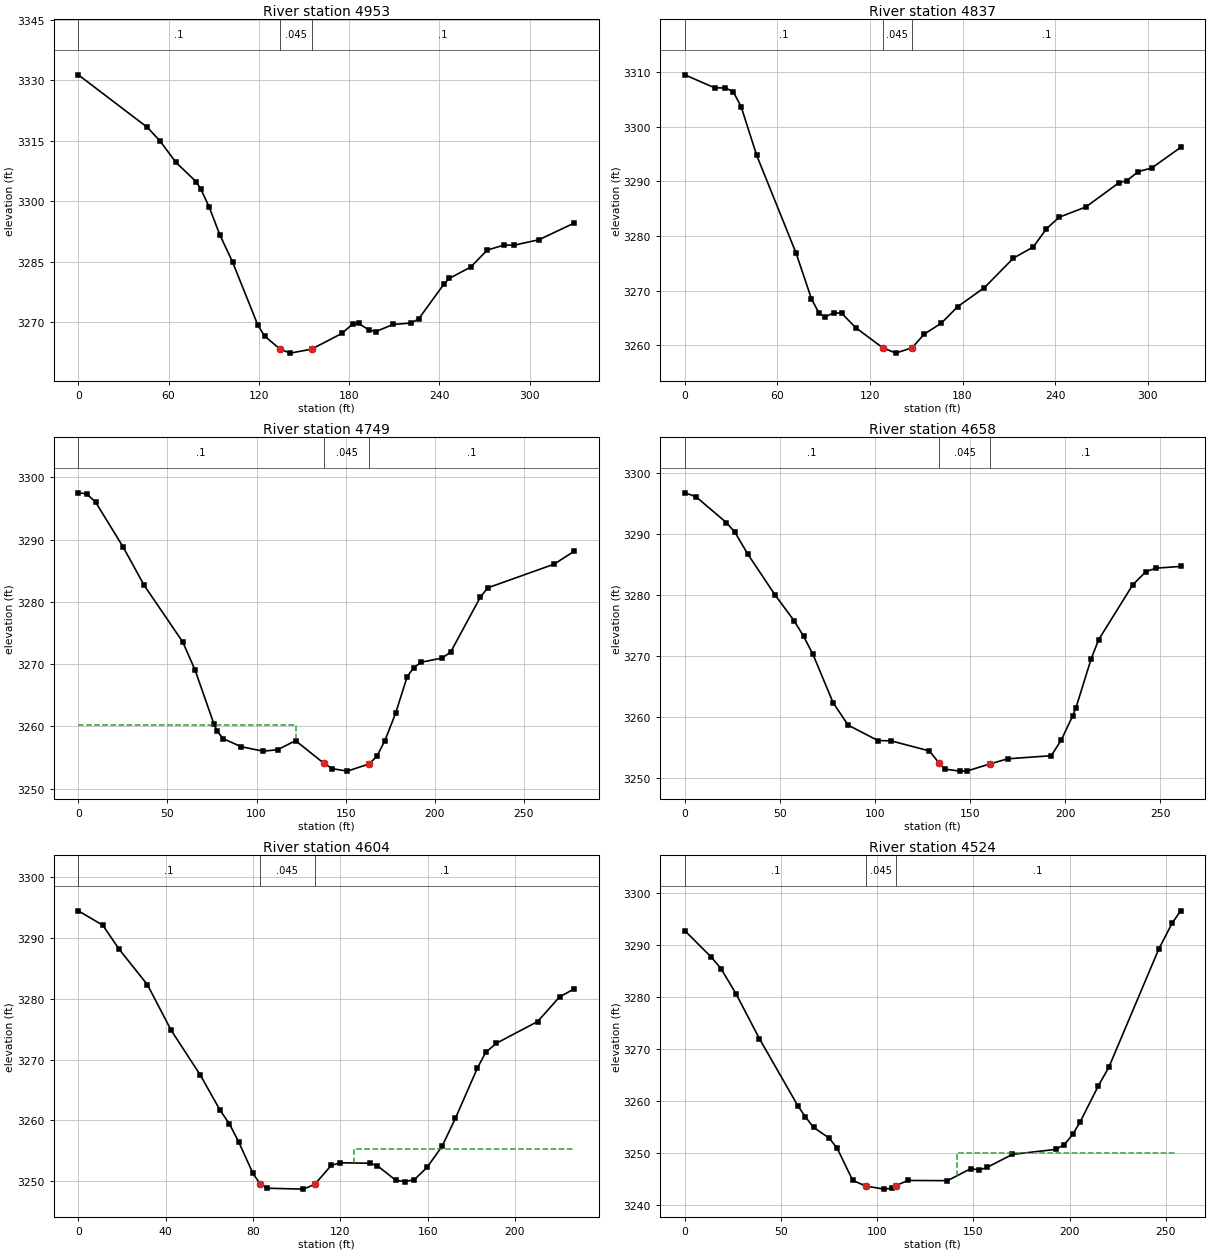
Type RM Length L Ch R = 1 ,4953    ,118.5,116.8,113.3
XS GIS Cut Line= 4
2194176.80196539 509647.704807592194239.47108841509706.457110422
2194368.72615464509834.4065699252194413.11678345509877.491592002
#Sta/Elev= 30
       0 3331.35    45.9 3318.33    54.4  3314.9    64.9 3309.65    78.2 3304.91
    81.4 3303.05    86.9 3298.68      94 3291.74   102.5 3284.98   119.4 3269.25
   123.9 3266.58  134.123263.365   140.9 3262.38  155.043263.364   175.1 3267.25
   182.6 3269.65   186.4 3269.73     193 3268.17   197.8 3267.73   209.2 3269.48
   221.3 3269.84   226.2 3270.85   243.3 3279.62   246.7 3280.91   260.9 3283.73
   271.8 3287.92   283.2 3289.18   289.3  3289.1   306.2 3290.48   329.6 3294.61
#Mann= 3 ,-1,0
       0      .1       0  134.12    .045       0  155.04      .1       0
Bank Sta=134.12,155.04
XS Rating Curve= 0 ,0
Exp/Cntr(USF)=0,0
Exp/Cntr=0.3,0.1

Type RM Length L Ch R = 1 ,4837    ,94.1,87.4,83.7
XS GIS Cut Line= 4
2194111.52162891509762.598199796 2194172.8851452509810.905648792
2194279.94489703 509885.325232382194385.69904213509924.493434268
#Sta/Elev= 30
       0 3309.46    19.4 3307.08    26.3 3307.06    31.4 3306.37    36.5 3303.64
    46.6 3294.72    72.1 3276.85    82.1 3268.46      87 3265.85    90.7 3265.17
    96.7 3265.93   101.6 3265.85   110.8  3263.2  128.183259.546   136.7 3258.55
  147.353259.545   155.2 3262.04   166.2 3264.02   176.9 3267.07   194.2 3270.54
     213 3275.94   225.8 3277.96   234.3 3281.28   242.6 3283.41   259.9 3285.29
   281.2 3289.69   286.4 3290.11     294 3291.77   302.6 3292.42   321.3 3296.18
#Mann= 3 ,-1,0
       0      .1       0  128.18    .045       0  147.35      .1       0
Bank Sta=128.18,147.35
XS Rating Curve= 0 ,0
Exp/Cntr(USF)=0,0
Exp/Cntr=0.3,0.1

Type RM Length L Ch R = 1 ,4749    ,60.3,90.9,115.7
XS GIS Cut Line= 3
2194068.52990698509844.8186162572194163.98996225509920.347451201
2194315.04763214509961.258903462
#Sta/Elev= 30
       0  3297.5     4.6 3297.35     9.7    3296    25.1 3288.82      37 3282.62
    58.6 3273.54    65.5 3269.04    76.1 3260.37    77.9 3259.23    81.2 3258.03
    91.4 3256.73   103.7 3256.01   111.8 3256.25   121.9  3257.7   137.9 3254.04
   142.6  3253.2   150.9 3252.81   163.13253.957   167.5 3255.18     172 3257.71
     178 3262.09   184.5 3267.97   188.2 3269.43   192.4  3270.3   204.1 3270.97
   208.9 3271.92   225.5 3280.72   229.7 3282.24     267 3286.05   278.2 3288.12
#Mann= 3 ,-1,0
       0      .1       0   137.9    .045       0   163.1      .1       0
#XS Ineff= 2 , 0
          122.37 3260.15
Permanent Ineff=
       F       F
Bank Sta=137.9,163.1
XS Rating Curve= 0 ,0
Exp/Cntr(USF)=0,0
Exp/Cntr=0.3,0.1

Type RM Length L Ch R = 1 ,4658    ,58.3,54,49.2
XS GIS Cut Line= 4
2194061.90857318509852.6850641392194129.52089692509935.708073505
 2194135.3546918510032.9040549532194173.02858501510074.638208174
#Sta/Elev= 30
       0  3296.8     5.8 3296.18    21.9 3291.91    26.4 3290.31    33.2 3286.71
    47.5 3280.03    57.4 3275.86    62.5 3273.25    67.4  3270.3      78 3262.37
    85.9  3258.7   101.5 3256.18   108.5 3256.12   128.6 3254.47   133.7 3252.48
   136.6  3251.5   144.6 3251.16   148.6  3251.2   160.6 3252.36   169.8 3253.18
   192.7 3253.69   197.9 3256.24   203.9 3260.19   205.7 3261.59   213.7 3269.61
   217.6 3272.72   235.5  3281.7   242.5 3283.89   247.9 3284.45   260.7 3284.73
#Mann= 3 ,-1,0
       0      .1       0   133.7    .045       0   160.6      .1       0
Bank Sta=133.7,160.6
XS Rating Curve= 0 ,0
Exp/Cntr(USF)=0,0
Exp/Cntr=0.3,0.1

Type RM Length L Ch R = 1 ,4604    ,78.7,80.2,81.9
XS GIS Cut Line= 4
2194039.82661837509887.1471503622194069.20276978509945.899453194
2194104.45415148510046.9534140672194150.28094769510076.329565483
#Sta/Elev= 30
       0 3294.45    11.2 3292.08    18.7 3288.13    31.6 3282.33    42.5 3274.83
    55.9 3267.44    64.9 3261.69    69.2 3259.43    73.4 3256.51      80 3251.28
    83.2 3249.61    86.3 3248.86   103.1 3248.71   108.3 3249.49   115.8  3252.6
     120 3253.05   133.4 3252.96   136.9 3252.58   145.4 3250.16   149.7 3249.95
   153.9 3250.27   159.7 3252.28   166.6 3255.74   172.7 3260.34   182.8 3268.63
   186.6 3271.18   191.4 3272.67   210.4 3276.26   220.4  3280.3   227.1 3281.62
#Mann= 3 ,-1,0
       0      .1       0    83.2    .045       0   108.3      .1       0
#XS Ineff= 2 , 0
                          126.29         3255.25
Permanent Ineff=
       F       F
Bank Sta=83.2,108.3
XS Rating Curve= 0 ,0
Exp/Cntr(USF)=0,0
Exp/Cntr=0.3,0.1

Type RM Length L Ch R = 1 ,4524    ,143.8,145.9,147.6
XS GIS Cut Line= 4
2193992.40955925509898.3926152082193996.53771245509970.514158129
2194015.55482136510054.0964297462194060.03319853510143.322174577
#Sta/Elev= 30
       0  3292.8    13.8 3287.67    18.8 3285.49    26.8 3280.51    38.8 3271.98
    58.9 3258.98    62.7 3256.93    66.9 3254.91      75 3252.85    79.1 3250.96
    87.3 3244.69    94.2  3243.6   103.7 3243.02   107.8  3243.2109.64223243.693
     116 3244.69   136.5 3244.65   148.8 3246.99   152.9 3246.69     157 3247.19
   170.3 3249.71   192.7 3250.67   197.2 3251.55   201.6 3253.55   205.5 3255.98
     215 3262.95   220.4  3266.5   246.3 3289.21   253.2 3294.18   257.7 3296.61
#Mann= 3 ,-1,0
       0      .1       0    94.2    .045       0109.6422      .1       0
#XS Ineff= 1 ,-1
  141.24255.0451 3249.94
Permanent Ineff=
       F
Bank Sta=94.2,109.6422
XS Rating Curve= 0 ,0
Exp/Cntr(USF)=0,0
Exp/Cntr=0.3,0.1