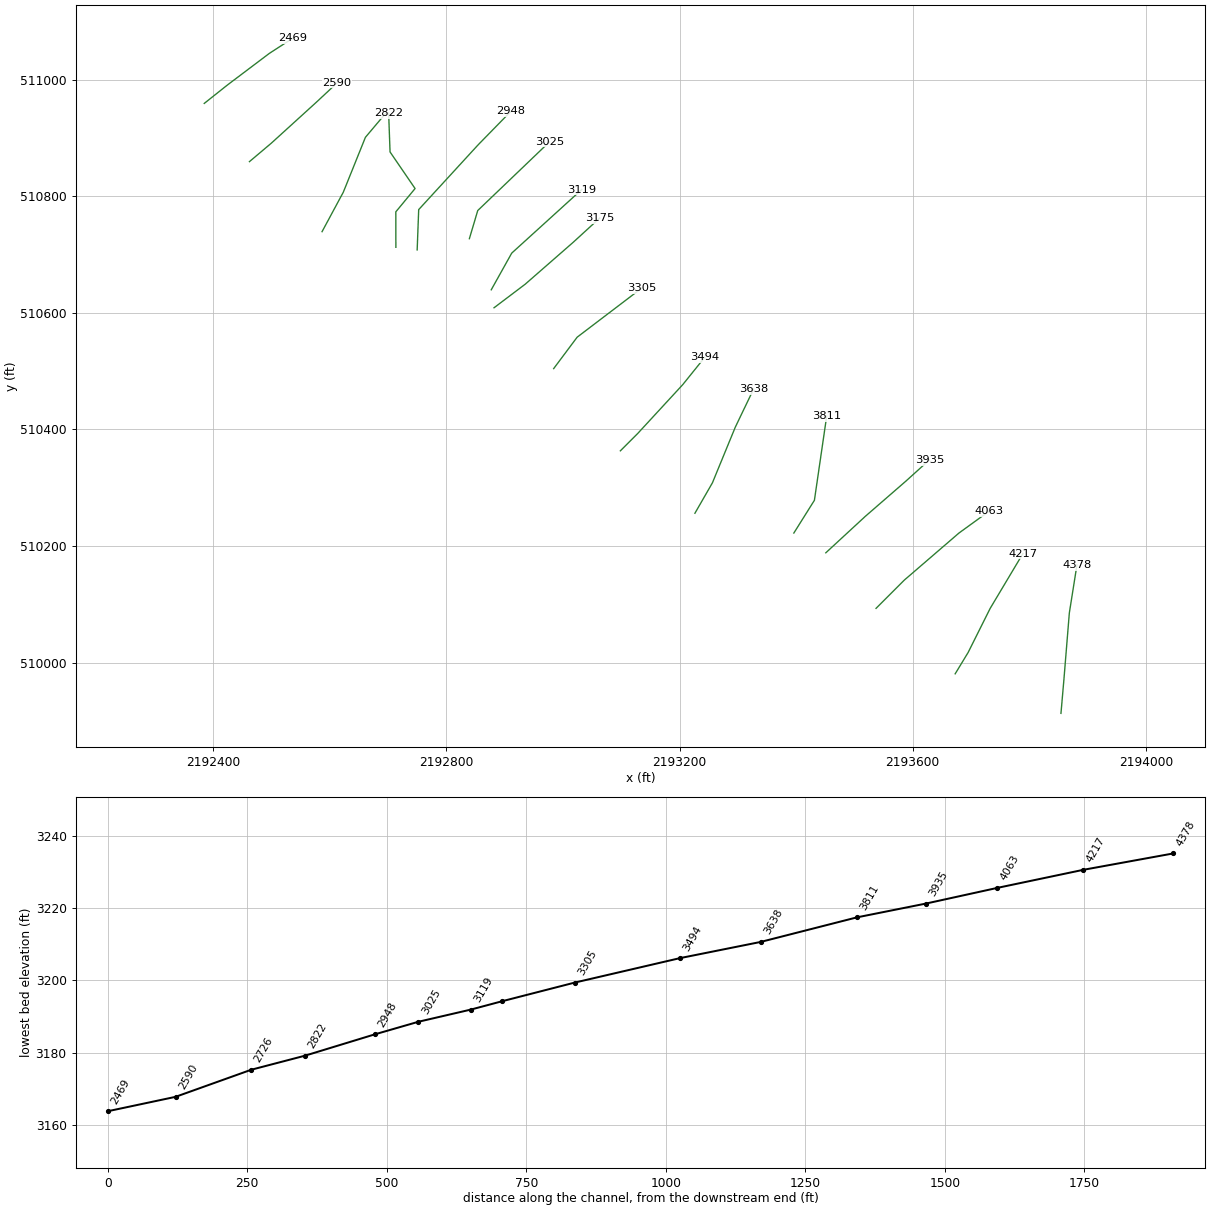
HEC-RAS study MFGAULYRV.prj: MFGAULYRV

--- MFGAULYRV.g01 (geometry) --- (continued)

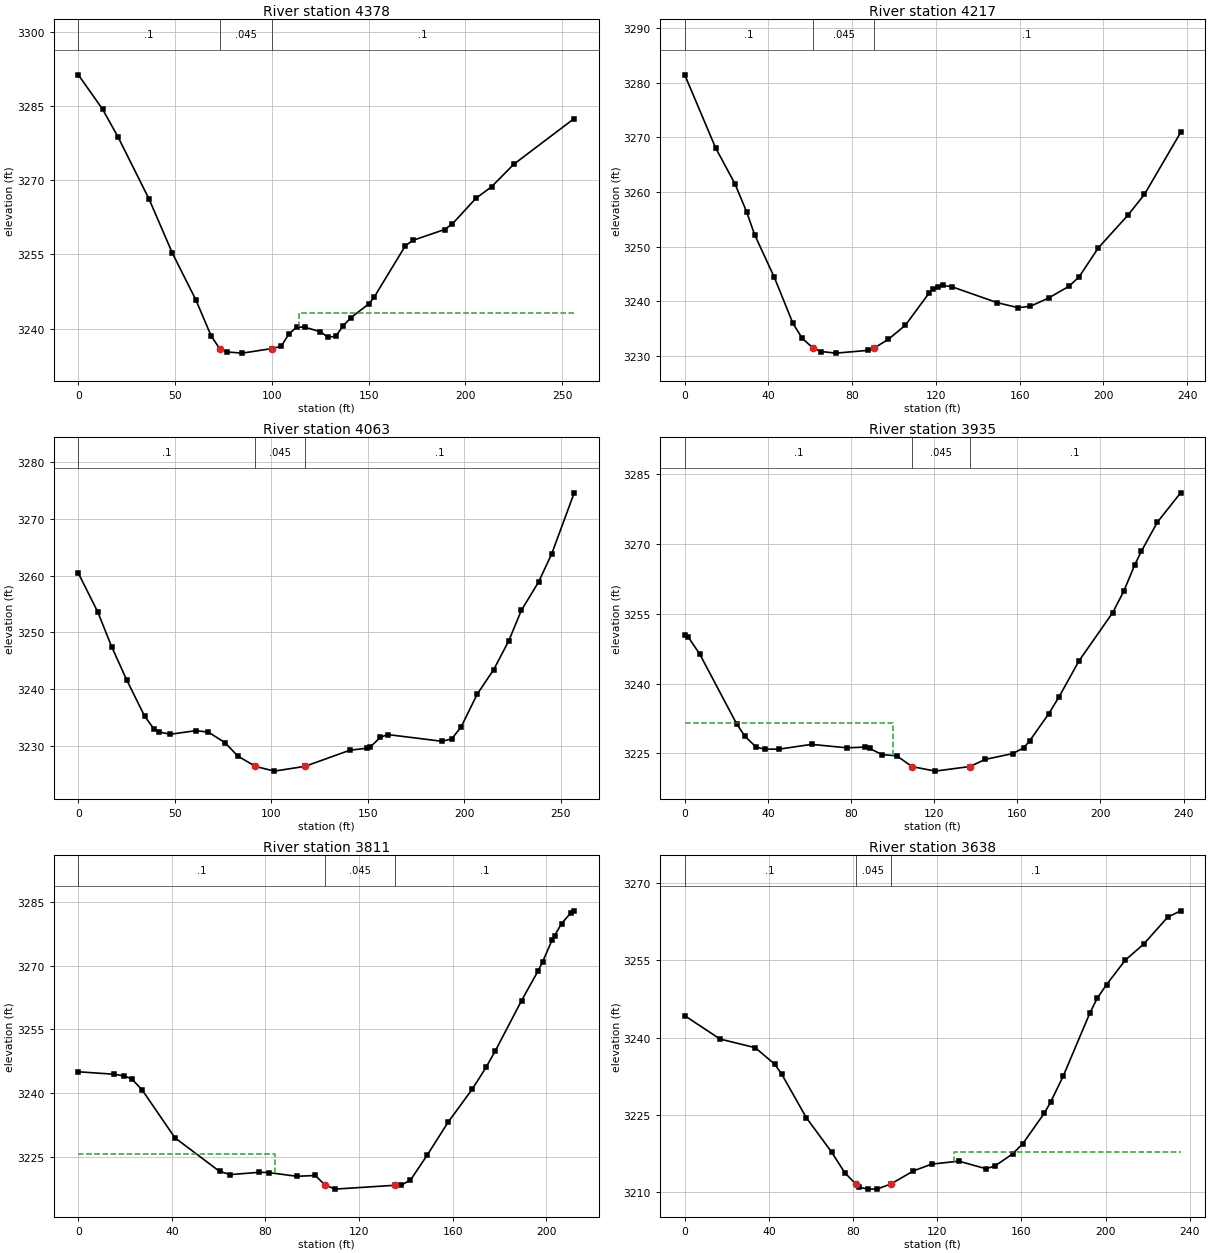
Type RM Length L Ch R = 1 ,4378    ,168.2,161.2,154
XS GIS Cut Line= 4
2193854.31710318509912.7429737022193859.53953009509972.800883264
 2193868.6787772510085.083062011 2193881.7348445510167.336285976
#Sta/Elev= 30
       0 3291.27    12.5 3284.34    20.5 3278.73    36.6 3266.13    48.6 3255.25
    60.7 3245.84    68.7 3238.47   73.023235.991    76.7 3235.31    84.7 3235.07
  100.073235.992   104.8 3236.46   108.8 3238.93   112.8 3240.34   116.9 3240.31
   124.9 3239.42   128.9 3238.33   132.9 3238.43   136.9 3240.61   140.9 3242.25
   150.3 3245.08     153 3246.47     169 3256.78     173 3257.86   189.2 3260.03
   193.3 3261.18   205.4 3266.33   213.5 3268.67     225 3273.22   256.2 3282.44
#Mann= 3 ,-1,0
       0      .1       0   73.02    .045       0  100.07      .1       0
#XS Ineff= 2 , 0
                          114.19         3243.15
Permanent Ineff=
       F       F
Bank Sta=73.02,100.07
XS Rating Curve= 0 ,0
Exp/Cntr(USF)=0,0
Exp/Cntr=0.3,0.1

Type RM Length L Ch R = 1 ,4217    ,162.1,154.2,146.6
XS GIS Cut Line= 4
2193672.83776776509980.6345236412193695.03308216510017.191512071
2193732.89567732510092.9167023882193789.03676669510186.920386921
#Sta/Elev= 30
       0 3281.43    14.7 3268.11      24 3261.49    29.6 3256.34    33.4 3252.18
    42.8  3244.4    51.7 3235.97    56.2 3233.22   61.513231.398    65.1 3230.83
    72.2 3230.54    87.5 3231.04   90.183231.399    97.3 3233.07   105.4 3235.64
   116.9 3241.61   118.8 3242.33   121.1 3242.67   123.3 3242.92   127.7 3242.67
   149.4 3239.75   159.2 3238.86     165 3239.09   173.8 3240.61   183.6 3242.77
   188.4 3244.49   197.6 3249.79   211.7 3255.76   219.6 3259.55   236.9 3270.89
#Mann= 3 ,-1,0
       0      .1       0   61.51    .045       0   90.18      .1       0
Bank Sta=61.51,90.18
XS Rating Curve= 0 ,0
Exp/Cntr(USF)=0,0
Exp/Cntr=0.3,0.1

Type RM Length L Ch R = 1 ,4063    ,127.5,127.7,127.9
XS GIS Cut Line= 4
2193537.05466788510092.9167023882193585.36211687510141.224151384
2193679.36580141 510222.171768622193731.59007059510260.034363779
#Sta/Elev= 30
       0 3260.45    10.1 3253.58    17.3 3247.45      25 3241.66    34.3 3235.26
    39.2 3232.95      42 3232.43    47.6 3232.04      61 3232.68    67.4 3232.41
      76 3230.55    82.6  3228.2   91.753226.377   101.5 3225.54  117.383226.378
   140.7 3229.23   149.7 3229.58   151.2 3229.79   156.5  3231.5   160.2 3231.99
   188.2 3230.81   193.4 3231.21   198.3 3233.32   206.6 3239.09   215.2 3243.45
     223 3248.52   229.5 3253.88   238.4 3258.87   245.2 3263.82   256.9 3274.61
#Mann= 3 ,-1,0
       0      .1       0   91.75    .045       0  117.38      .1       0
Bank Sta=91.75,117.38
XS Rating Curve= 0 ,0
Exp/Cntr(USF)=0,0
Exp/Cntr=0.3,0.1

Type RM Length L Ch R = 1 ,3935    ,110.8,124.1,138.5
XS GIS Cut Line= 4
2193450.88462372 510188.225993652193518.77617366510250.895116672
2193587.97333033510310.9530262342193628.44713895510347.510014663
#Sta/Elev= 30
       0 3250.47     1.8 3249.95     7.2 3246.37      25 3231.35      29 3228.68
    34.4 3226.36    38.4 3225.94    45.3 3225.93      61 3226.96      78 3226.22
    86.5 3226.37    88.9  3226.1      95 3224.75     102  3224.5  109.313222.197
   120.5 3221.21  137.123222.195   144.7 3223.74   157.8 3224.98   163.1 3226.22
   165.9 3227.67   175.2 3233.58   180.1 3237.17   189.7  3244.9   205.9 3255.26
   211.2 3259.83   216.6 3265.61   219.7 3268.45   227.4 3274.71   238.6 3281.02
#Mann= 3 ,-1,0
       0      .1       0  109.31    .045       0  137.12      .1       0
#XS Ineff= 2 , 0
          100.39 3231.45
Permanent Ineff=
       F       F
Bank Sta=109.31,137.12
XS Rating Curve= 0 ,0
Exp/Cntr(USF)=0,0
Exp/Cntr=0.3,0.1

Type RM Length L Ch R = 1 ,3811    ,174.9,172.6,170.3
XS GIS Cut Line= 3
2193396.04914108 510222.171768622193431.30052278510278.312857994
 2193452.3449858510422.476735113
#Sta/Elev= 30
       0 3245.01    15.3 3244.43    19.7 3244.02    22.8 3243.34    27.2  3240.8
    41.3 3229.47    60.4 3221.55      65  3220.8    77.3 3221.34    81.3 3221.29
    93.4  3220.4   101.3 3220.59105.33443218.437   109.6 3217.38135.32733218.286
   137.9 3218.28     142 3219.51   149.1 3225.35   158.1 3233.15   168.4 3240.91
   174.3 3246.05   178.3 3249.97   189.5 3261.79   196.6 3268.82   198.5 3270.92
   202.6 3276.11   203.6 3277.09   206.6  3279.9   210.6 3282.48     212 3282.91
#Mann= 3 ,-1,0
       0      .1       0105.3344    .045       0135.3273      .1       0
#XS Ineff= 2 , 0
           84.16 3225.76
Permanent Ineff=
       F       F
Bank Sta=105.3344,135.3273
XS Rating Curve= 0 ,0
Exp/Cntr(USF)=0,0
Exp/Cntr=0.3,0.1

Type RM Length L Ch R = 1 ,3638    ,149.9,144.7,139.6
XS GIS Cut Line= 4
2193226.32026623 510256.117543592193256.34922101510308.341812775
 2193295.5174229510403.6511040372193326.85198441510468.931440518
#Sta/Elev= 30
       0 3244.27    16.8 3239.73    33.5 3238.06    42.8 3234.83    46.1 3232.91
    57.8 3224.45    69.8 3217.78    76.1 3213.75   81.25 3211.59    82.8 3210.97
    87.1 3210.58    91.4 3210.59   98.033211.592   108.7 3214.12   117.4 3215.44
   130.3 3216.01   143.3 3214.53   147.6 3215.12   155.8 3217.42   160.6 3219.37
   170.9 3225.32   173.9 3227.48   179.9 3232.54   192.5 3244.73     196 3247.63
   200.5 3250.31   209.4 3255.06   218.2  3258.2   229.5 3263.39   235.7 3264.64
#Mann= 3 ,-1,0
       0      .1       0   81.25    .045       0   98.03      .1       0
#XS Ineff= 1 ,-1
  128.16 235.697 3217.82
Permanent Ineff=
       T
Bank Sta=81.25,98.03
XS Rating Curve= 0 ,0
Exp/Cntr(USF)=0,0
Exp/Cntr=0.3,0.1

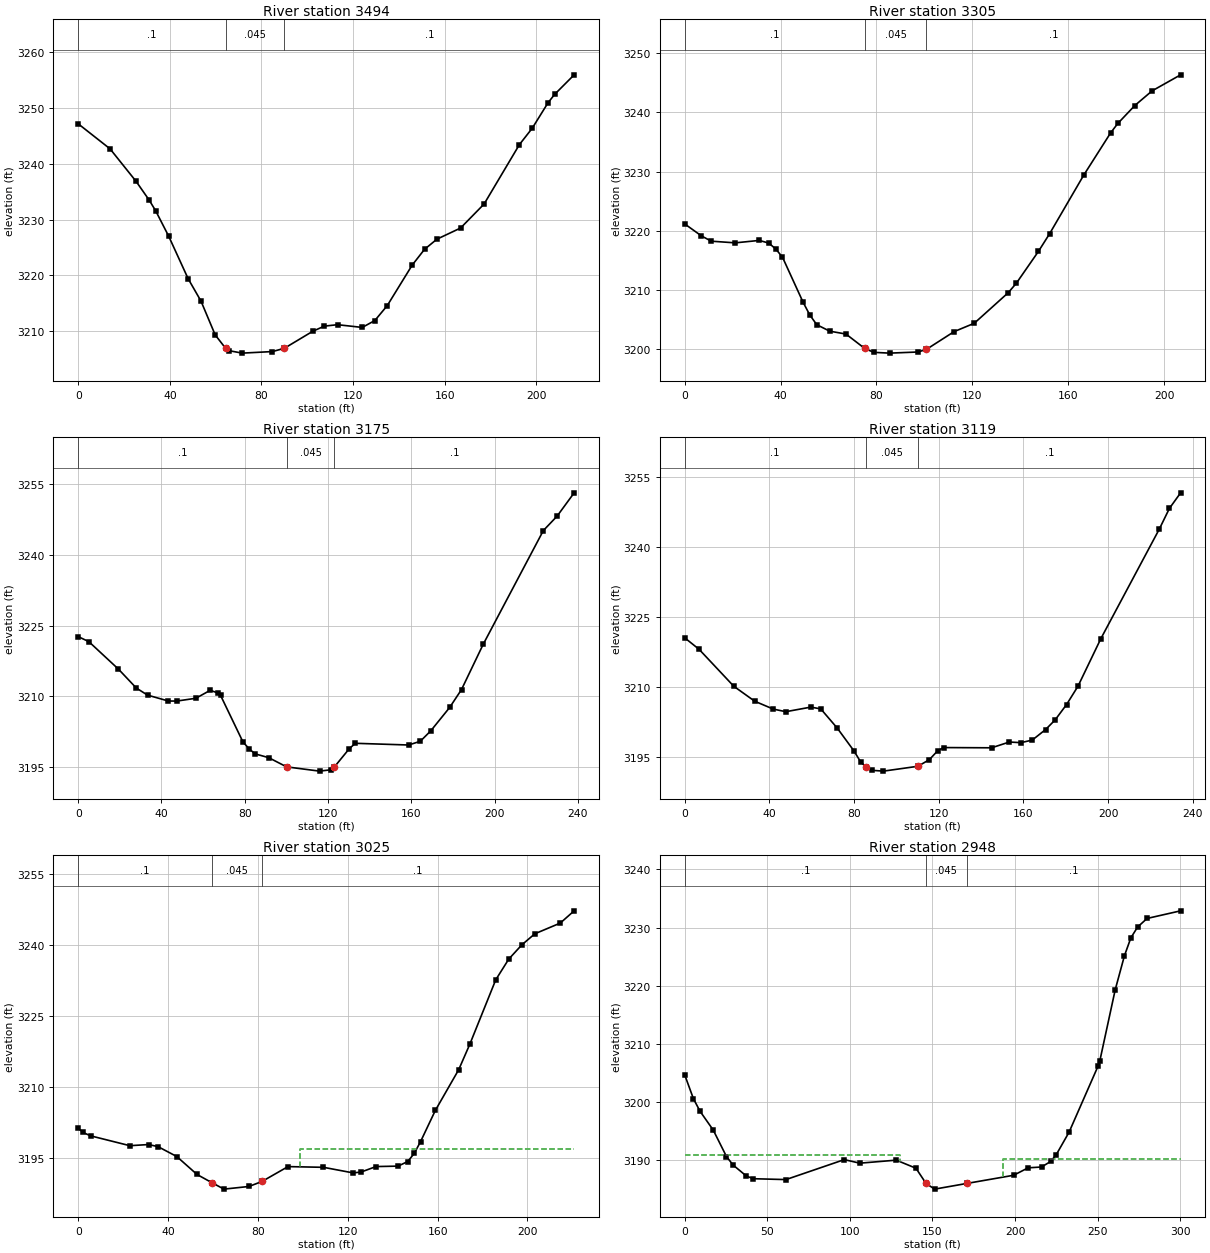
Type RM Length L Ch R = 1 ,3494    ,191.9,188.4,186.3
XS GIS Cut Line= 4
2193098.37080673510363.1772954192193128.39976151  510393.2062502
2193205.43055856510476.7650808952193243.29315372510523.766923161
#Sta/Elev= 30
       0 3247.15    13.9 3242.67    25.3 3236.83      31 3233.48    33.8 3231.59
    39.5 3227.03      48 3219.41    53.6 3215.41    59.8 3209.36   64.343206.967
    65.7 3206.55    71.6  3206.1    84.8 3206.38      903206.967   102.3 3209.99
   107.4 3210.93   113.2 3211.19     124  3210.7   129.5 3211.94   134.9  3214.6
   145.8 3221.86   151.2 3224.69   156.6  3226.5   166.9 3228.49   177.2  3232.8
   192.6 3243.43   198.2 3246.36   205.1 3250.92     208 3252.43   216.5 3255.92
#Mann= 3 ,-1,0
       0      .1       0   64.34    .045       0      90      .1       0
Bank Sta=64.34,90
XS Rating Curve= 0 ,0
Exp/Cntr(USF)=0,0
Exp/Cntr=0.3,0.1

Type RM Length L Ch R = 1 ,3305    ,129.3,130.2,131
XS GIS Cut Line= 3
2192983.96797372510504.2620309412193024.23886273510558.146501834
2193135.41835436 510642.65634428
#Sta/Elev= 30
       0 3221.16       7 3219.13    11.1 3218.24    21.1 3217.96    31.1 3218.37
    35.1 3217.92      38 3216.92    40.8 3215.54    49.4 3207.93    52.2 3205.78
    55.1 3204.14    60.5 3203.05    67.3 3202.56    75.1 3200.13    78.9 3199.47
    85.5 3199.34    97.3 3199.53   100.8 3199.96   112.4 3202.97   120.8 3204.38
     135 3209.55   138.4 3211.16   147.6 3216.53   152.2 3219.47   166.4 3229.34
   177.7 3236.53   180.7 3238.12   187.8 3241.15     195 3243.62   206.9 3246.33
#Mann= 3 ,-1,0
       0      .1       0    75.1    .045       0   100.8      .1       0
Bank Sta=75.1,100.8
XS Rating Curve= 0 ,0
Exp/Cntr(USF)=0,0
Exp/Cntr=0.3,0.1

Type RM Length L Ch R = 1 ,3175    ,55.7,55.8,56.3
XS GIS Cut Line= 4
2192881.64008961510608.6313605862192935.16996553510649.105169205
2193017.42318949510720.9135393332193063.11942503510762.692954681
#Sta/Elev= 30
       0 3222.65     5.1 3221.59    19.3 3215.78    27.9 3211.77    33.3 3210.27
    43.3 3209.02    47.3 3209.01    56.5  3209.6    63.4 3211.29    67.1 3210.72
    68.4 3210.19    79.1 3200.38      82 3198.94    84.9 3197.84    91.5 3197.03
  100.093195.082   115.9 3194.18   121.5 3194.47  123.073195.084   130.2 3198.93
   133.1 3200.07   158.7 3199.71   164.3  3200.5   169.3 3202.69   178.4 3207.65
   184.1 3211.45   194.5 3221.01   223.4  3245.1     230 3248.15   238.2 3253.09
#Mann= 3 ,-1,0
       0      .1       0  100.09    .045       0  123.07      .1       0
Bank Sta=100.09,123.07
XS Rating Curve= 0 ,0
Exp/Cntr(USF)=0,0
Exp/Cntr=0.3,0.1

Type RM Length L Ch R = 1 ,3119    ,93.4,94,94.3
XS GIS Cut Line= 3
2192876.85273343510639.4449005582192911.99462191510702.385596344
 2193032.1064497510811.482802373
#Sta/Elev= 30
       0 3220.46     6.8 3217.99    23.2 3210.07    33.1 3206.86    41.9 3205.17
    47.8 3204.62    59.6  3205.6    64.3 3205.22    72.1 3201.09    79.9 3196.26
    83.1 3193.88    85.5 3192.84    88.5 3192.05    93.9 3191.88   110.2 3192.92
   115.6 3194.34   119.5 3196.23   122.3 3196.93     145 3196.88   153.4 3198.12
   158.8 3197.98   164.2 3198.53   170.5 3200.79     175 3202.85   180.4 3206.14
   185.8 3210.07   196.6 3220.26   224.3 3243.82     229 3248.19   234.3 3251.53
#Mann= 3 ,-1,0
       0      .1       0    85.5    .045       0   110.2      .1       0
Bank Sta=85.5,110.2
XS Rating Curve= 0 ,0
Exp/Cntr(USF)=0,0
Exp/Cntr=0.3,0.1

Type RM Length L Ch R = 1 ,3025    ,75.9,77.2,78.2
XS GIS Cut Line= 3
2192839.33616846510727.1320622882192853.69784249510775.439511284
2192976.79462553 510893.30255187
#Sta/Elev= 30
       0 3201.38     2.1 3200.47     5.5 3199.75      23 3197.67    31.3 3197.91
    35.5 3197.48    43.9 3195.38    52.9  3191.6    59.4  3189.9    64.9 3188.51
      76 3189.07    81.8 3190.12    93.4 3193.26   109.2 3193.11   122.3 3191.94
   125.8 3192.09   132.6 3193.27   142.4 3193.36   146.7 3194.33   149.6 3196.04
   152.4 3198.51     159 3205.11   169.4  3213.7   174.4 3219.13   185.9 3232.66
   191.7 3237.03   197.5 3240.02   203.3 3242.36   214.6 3244.61   220.8  3247.2
#Mann= 3 ,-1,0
       0      .1       0    59.4    .045       0    81.8      .1       0
#XS Ineff= 2 , 0
                           98.87         3196.89
Permanent Ineff=
       F       F
Bank Sta=59.4,81.8
XS Rating Curve= 0 ,0
Exp/Cntr(USF)=0,0
Exp/Cntr=0.3,0.1

Type RM Length L Ch R = 1 ,2948    ,94.2,126.2,143.5
XS GIS Cut Line= 4
2192749.77380992510707.8574720372192752.38502338510777.054628707
2192854.22234829510888.0312007242192910.36343766510945.477896827
#Sta/Elev= 30
       0 3204.72     5.3  3200.6     9.3 3198.45    17.3 3195.21    25.3 3190.67
    29.3 3189.21    37.3 3187.33    41.4 3186.86    61.3 3186.71    96.6 3190.14
     106 3189.53   128.1 3190.05     140 3188.66  146.113186.044   151.3 3185.07
  170.753186.045   199.1 3187.45   207.9 3188.73     216 3188.87   221.5 3189.82
   224.9 3190.98   232.7 3194.87   250.3 3206.26   251.3 3207.12   260.6 3219.32
   266.2 3225.18   270.1 3228.26   274.2 3230.12   279.9 3231.58   300.2 3232.89
#Mann= 3 ,-1,0
       0      .1       0  146.11    .045       0  170.75      .1       0
#XS Ineff= 2 ,-1
       0  130.53    3191  192.91300.1913 3190.27
Permanent Ineff=
       F       F
Bank Sta=146.11,170.75
XS Rating Curve= 0 ,0
Exp/Cntr(USF)=0,0
Exp/Cntr=0.3,0.1

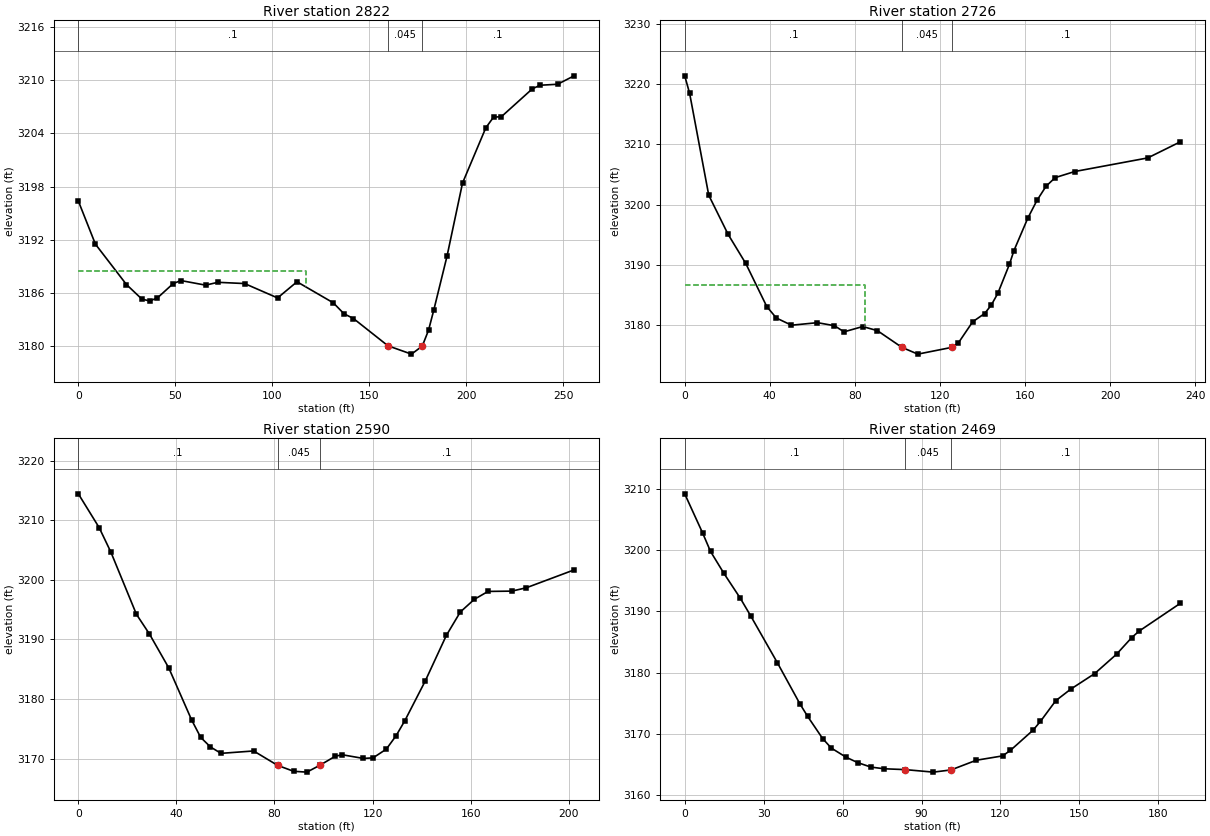
Type RM Length L Ch R = 1 ,2822    ,111,96.1,77.3
XS GIS Cut Line= 5
2192713.22602635510712.3768308022192713.14643629510773.244908559
2192746.18490685510813.1666336542192703.24131422510875.997015554
2192700.83238694510942.627570293
#Sta/Elev= 30
       0 3196.37     8.8 3191.51    24.8 3186.96    32.8 3185.31    36.8 3185.11
    40.8 3185.46    48.8 3187.05    52.8 3187.41    65.6 3186.89    71.9 3187.21
    85.7 3187.07   102.7 3185.45   112.7 3187.27   131.4  3184.9   136.9 3183.67
   141.8 3183.13  159.56 3180.06   171.7 3179.12177.26663180.027   180.5 3181.82
   183.2 3184.09     190 3190.14     198 3198.39     210 3204.61     214 3205.82
     218 3205.86     234 3209.01     238 3209.41     247 3209.52   255.5 3210.47
#Mann= 3 ,-1,0
       0      .1       0  159.56    .045       0177.2666      .1       0
#XS Ineff= 2 , 0
          117.53  3188.5
Permanent Ineff=
       F       F
Bank Sta=159.56,177.2666
XS Rating Curve= 0 ,0
Exp/Cntr(USF)=0,0
Exp/Cntr=0.3,0.1

Type RM Length L Ch R = 1 ,2726    ,141.8,135.6,128
XS GIS Cut Line= 4
2192586.57296872510739.1920335482192623.12995715510807.083583488
2192660.99255231 510901.087268022192696.24393401510942.866683368
#Sta/Elev= 30
       0 3221.34     2.3 3218.45    11.3 3201.56    20.4 3195.08    28.7 3190.26
    38.6 3183.11    43.1 3181.22    50.2 3180.03    62.4 3180.45    70.4 3179.95
    74.9 3178.93    83.7 3179.81    90.6 3179.13  102.12 3176.36   109.6 3175.24
  125.613176.361   128.7 3177.11   135.4  3180.6     141 3181.96   144.1 3183.34
   147.2 3185.29   152.7 3190.14   154.8 3192.39   161.3 3197.75   165.6 3200.69
   169.9 3203.05   174.2 3204.48   183.4 3205.49   217.7 3207.74   233.1 3210.42
#Mann= 3 ,-1,0
       0      .1       0  102.12    .045       0  125.61      .1       0
#XS Ineff= 2 , 0
           84.71 3186.73
Permanent Ineff=
       F       F
Bank Sta=102.12,125.61
XS Rating Curve= 0 ,0
Exp/Cntr(USF)=0,0
Exp/Cntr=0.3,0.1

Type RM Length L Ch R = 1 ,2590    ,122.7,121.4,120.2
XS GIS Cut Line= 4
2192462.04334191510859.3826668752192499.64481572510891.108910404
2192577.19785546510961.6116738042192612.44923716 510994.51296339
#Sta/Elev= 30
       0 3214.43     8.5 3208.76    13.3 3204.63    23.7 3194.22      29 3190.92
    36.9 3185.22    46.2 3176.51    49.9 3173.58    53.9 3171.97    58.2  3170.9
    71.5  3171.3   81.263168.888    87.8 3167.89    93.2 3167.75   98.473168.888
   104.8 3170.42   107.7 3170.66   116.2 3170.05   120.2 3170.14   125.6  3171.6
   129.6 3173.85   133.2  3176.4   141.5 3183.04   150.1 3190.68   155.8 3194.61
   161.5 3196.73   167.1 3198.06   176.8 3198.11   182.7 3198.67   202.2 3201.67
#Mann= 3 ,-1,0
       0      .1       0   81.26    .045       0   98.47      .1       0
Bank Sta=81.26,98.47
XS Rating Curve= 0 ,0
Exp/Cntr(USF)=0,0
Exp/Cntr=0.3,0.1

Type RM Length L Ch R = 1 ,2469    ,119.9,118.4,116.5
XS GIS Cut Line= 4
2192384.49030217 510959.26158169 2192424.4418681 510990.98782522
2192496.11967755511045.0399438262192536.07124348511070.890957072
#Sta/Elev= 30
       0 3209.21     6.8 3202.82     9.8 3199.81    14.9 3196.22    21.1 3192.18
    25.1 3189.26    35.2 3181.64    43.8  3174.9    46.7 3172.88    52.4 3169.26
    55.7  3167.7    61.3 3166.21    65.7 3165.33    70.7  3164.6    75.7 3164.32
    83.8 3164.18    94.5 3163.77   101.2 3164.13   110.8 3165.71   120.8 3166.42
   123.8 3167.33   132.4 3170.63   135.2 3172.06     141 3175.43   146.7 3177.32
   155.8 3179.86   164.1 3183.02   169.9 3185.75   172.7  3186.8   188.4 3191.35
#Mann= 3 ,-1,0
       0      .1       0    83.8    .045       0   101.2      .1       0
Bank Sta=83.8,101.2
XS Rating Curve= 0 ,0
Exp/Cntr(USF)=0,0
Exp/Cntr=0.3,0.1