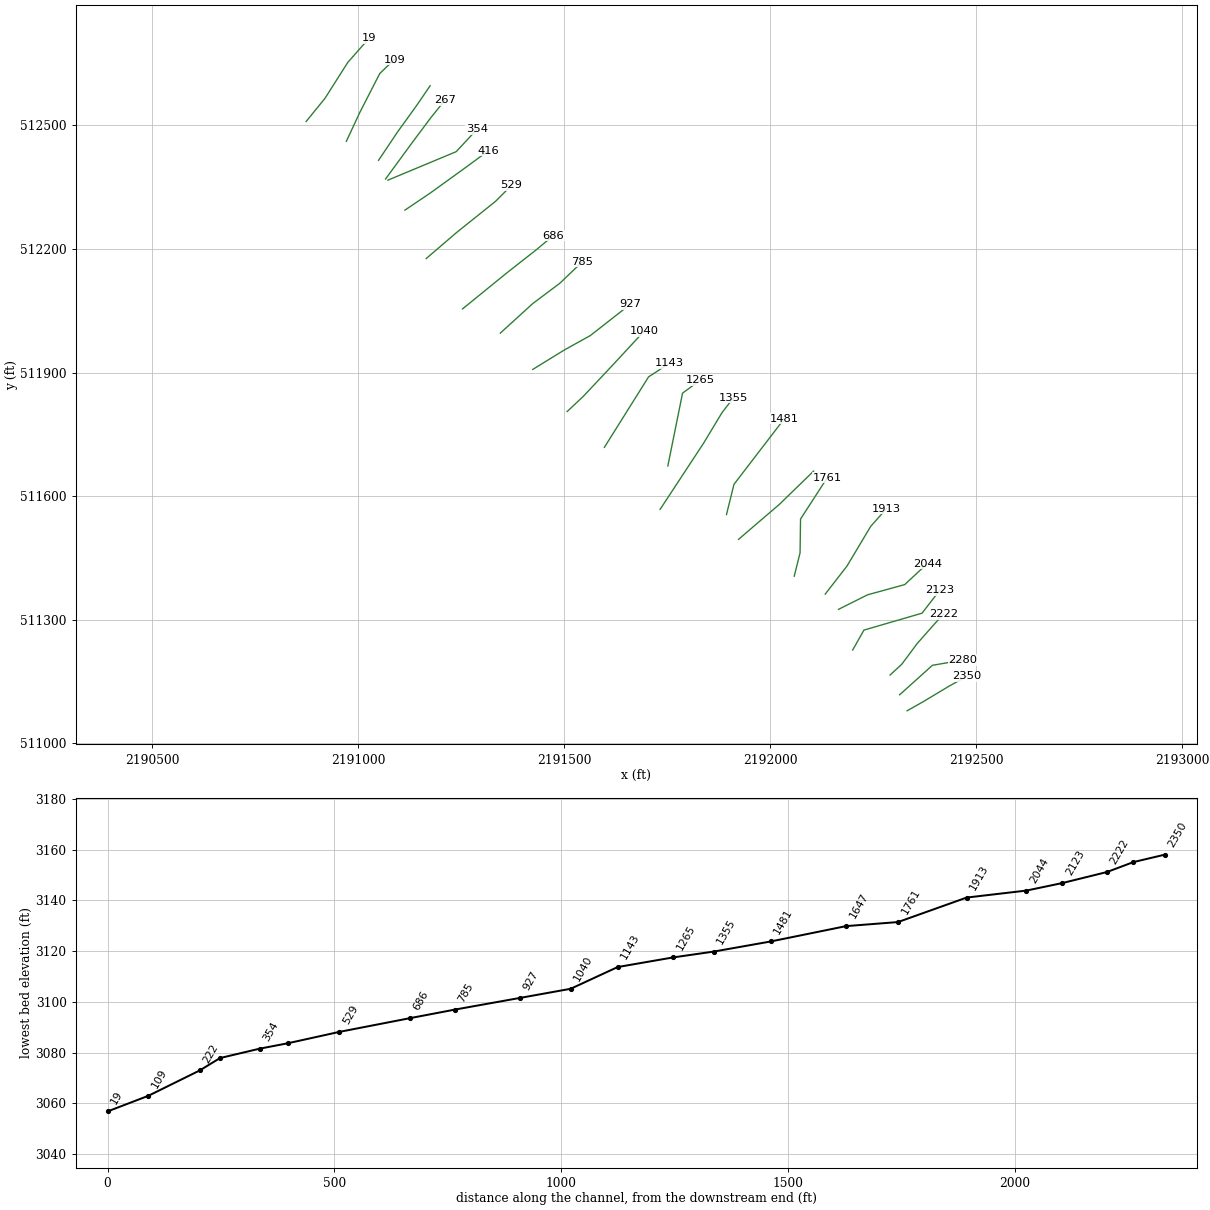
HEC-RAS study MFGAULYRV.prj: MFGAULYRV

--- MFGAULYRV.g01 (geometry) --- (continued)

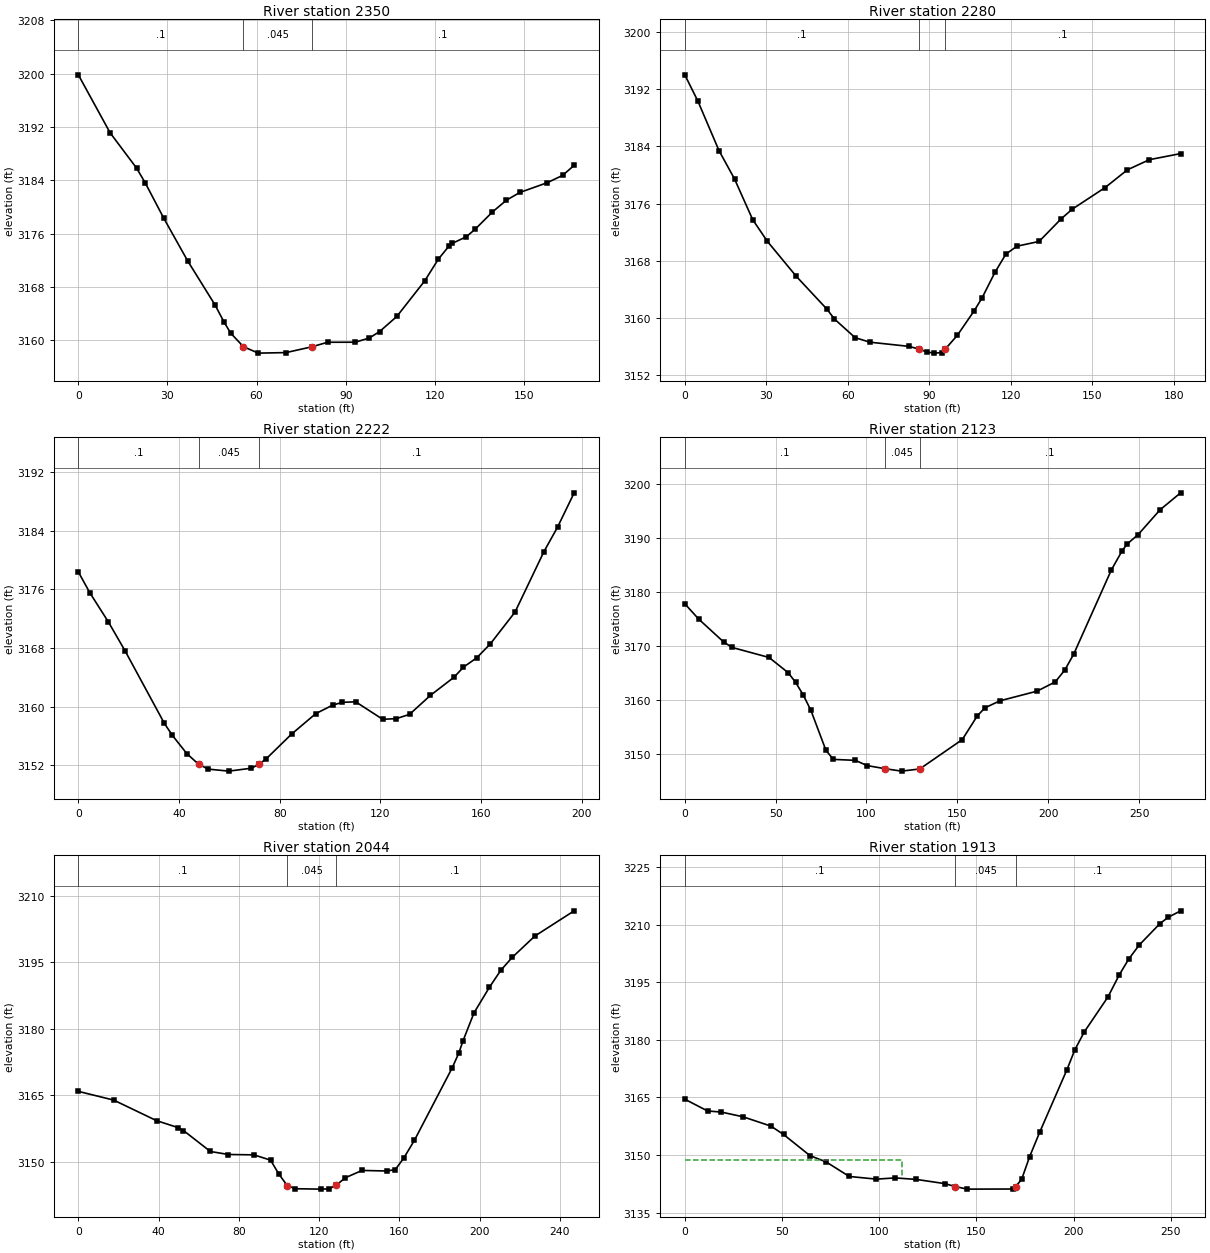
Type RM Length L Ch R = 1 ,2350    ,55.8,70.3,67.2
XS GIS Cut Line= 4
2192331.61322962511079.1162794692192369.21470343511100.267108489
2192433.84223655511139.0436283582192476.14389459511162.544549491
#Sta/Elev= 30
       0 3199.84    10.7 3191.14    19.6 3185.85    22.5 3183.65    28.7 3178.38
    36.8 3171.93      46 3165.33    49.1 3162.71    51.3 3161.08   55.593159.046
    60.6 3158.09    69.9 3158.17   78.663159.045    83.9 3159.72    93.2 3159.73
    97.9 3160.35   101.4 3161.32   107.2 3163.59   116.6 3168.93   121.2  3172.2
   124.7 3174.11   125.8 3174.54   130.6 3175.55   133.6 3176.69   139.4 3179.27
   144.1 3181.03   148.6 3182.19   157.8 3183.65     163 3184.75   166.9 3186.26
#Mann= 3 ,-1,0
       0      .1       0   55.59    .045       0   78.66      .1       0
Bank Sta=55.59,78.66
XS Rating Curve= 0 ,0
Exp/Cntr(USF)=0,0
Exp/Cntr=0.3,0.1

Type RM Length L Ch R = 1 ,2280    ,52.8,58.2,60
XS GIS Cut Line= 3
 2192313.5499153511117.9656762612192393.15206303511189.528770892
2192467.56799272 511202.27044743
#Sta/Elev= 30
       0 3194.01     4.8 3190.35    12.6 3183.41    18.3 3179.46      25 3173.76
    30.4 3170.73      41 3165.86    52.3 3161.26    55.1 3159.87    62.7 3157.27
    68.1 3156.64    82.6 3156.05    86.3 3155.66    89.1 3155.26    91.9 3155.11
    94.6 3155.19   95.85 3155.67   100.3 3157.59   106.5 3161.02   109.4 3162.82
   114.2 3166.43   118.2 3168.96   122.3 3170.06   130.4 3170.72   138.5 3173.87
   142.6 3175.23   154.7 3178.25   162.9 3180.73     171 3182.15   182.5    3183
#Mann= 3 ,-1,0
       0      .1       0    86.3    .045       0   95.85      .1       0
Bank Sta=86.3,95.85
XS Rating Curve= 0 ,0
Exp/Cntr(USF)=0,0
Exp/Cntr=0.3,0.1

Type RM Length L Ch R = 1 ,2222    ,109.5,98.4,88.7
XS GIS Cut Line= 4
2192290.48661764511166.069687661  2192318.687723511191.920700908
2192356.28919681511242.4476813442192419.74168387  511314.1254908
#Sta/Elev= 30
       0 3178.36     4.6  3175.5    11.9 3171.56    18.6 3167.58    34.2  3157.7
    37.4 3156.06    43.1 3153.59   47.86 3152.11    51.7 3151.47    59.8  3151.2
    68.8  3151.6   71.653152.109    74.5 3152.83    84.7 3156.24    94.3 3159.03
     101 3160.19   104.9 3160.58   110.2 3160.65   120.9 3158.27   126.3 3158.35
   131.6 3158.94   139.9 3161.53   149.3 3164.01     153 3165.37   158.3 3166.65
   163.7 3168.55   173.5 3172.88     185 3181.13   190.4 3184.46     197 3189.14
#Mann= 3 ,-1,0
       0      .1       0   47.86    .045       0   71.65      .1       0
Bank Sta=47.86,71.65
XS Rating Curve= 0 ,0
Exp/Cntr(USF)=0,0
Exp/Cntr=0.3,0.1

Type RM Length L Ch R = 1 ,2123    ,79.5,79.3,79.4
XS GIS Cut Line= 4
2192199.60718809511226.5673081242192226.95889873511274.958796174
 2192367.9254074 511315.98636213 2192411.0569511511371.741772275
#Sta/Elev= 30
       0 3177.78     7.6 3174.96    21.4 3170.71      26 3169.71    46.4 3167.85
    56.9 3165.04      61 3163.25    65.2 3160.92    69.4 3158.08    77.7 3150.68
    81.8 3149.02    93.9 3148.84   100.3 3147.88     110 3147.31   119.3 3146.85
   129.3 3147.25   152.7 3152.67     161 3157.06   165.2 3158.55   173.5 3159.85
   193.9 3161.63   203.9 3163.34   209.1 3165.51     214 3168.43   234.8 3184.05
   240.5 3187.44   243.3 3188.78   249.4 3190.52   261.6 3195.15   272.9 3198.28
#Mann= 3 ,-1,0
       0      .1       0     110    .045       0   129.3      .1       0
Bank Sta=110,129.3
XS Rating Curve= 0 ,0
Exp/Cntr(USF)=0,0
Exp/Cntr=0.3,0.1

Type RM Length L Ch R = 1 ,2044    ,116.5,131.6,146.9
XS GIS Cut Line= 4
2192165.30697875511325.3121312372192235.80974215511360.563512936
2192325.89660649511385.3700407992192380.73208913511436.288703254
#Sta/Elev= 30
       0  3165.9    17.6 3163.94      39  3159.3    49.7 3157.74    52.4 3157.08
    65.8 3152.36    74.8 3151.68    87.5  3151.6    95.8 3150.41    99.9  3147.3
   104.1 3144.68   108.2 3143.97   120.7 3143.88   124.8 3143.93   128.4 3144.73
   133.1 3146.45   141.4 3148.09   153.9 3147.96     158  3148.3   162.2 3150.89
   167.5 3154.88   186.3 3171.18   189.6 3174.51   191.7 3177.28   197.2  3183.6
   204.9 3189.37   210.5 3193.15   216.2 3196.07   227.5 3200.88   247.1 3206.57
#Mann= 3 ,-1,0
       0      .1       0   104.1    .045       0   128.4      .1       0
Bank Sta=104.1,128.4
XS Rating Curve= 0 ,0
Exp/Cntr(USF)=0,0
Exp/Cntr=0.3,0.1

Type RM Length L Ch R = 1 ,1913    ,140.4,151.3,162
XS GIS Cut Line= 4
2192133.03044605511362.302379123 2192185.9075186511430.455050408
2192243.48477537511526.8088270542192281.08624919511569.110485094
#Sta/Elev= 30
       0 3164.54    11.7 3161.48    18.8 3161.19    29.9 3159.97    44.3 3157.54
    50.8 3155.36    64.4 3149.85    72.7 3148.22    84.6 3144.43    98.6 3143.73
   108.1 3144.05   119.1 3143.66   133.7 3142.57  139.143141.807   145.3 3141.13
   168.7 3141.16  170.223141.805   173.3 3143.67   177.4 3149.57   182.6 3155.96
   196.6 3172.21   200.7 3177.43   205.6 3182.11   217.7 3191.15   223.6 3196.97
   228.4 3201.02   233.8 3204.68   244.5 3210.28   248.8 3211.92   255.1 3213.58
#Mann= 3 ,-1,0
       0      .1       0  139.14    .045       0  170.22      .1       0
#XS Ineff= 2 , 0
          111.88 3148.73
Permanent Ineff=
       F       F
Bank Sta=139.14,170.22
XS Rating Curve= 0 ,0
Exp/Cntr(USF)=0,0
Exp/Cntr=0.3,0.1

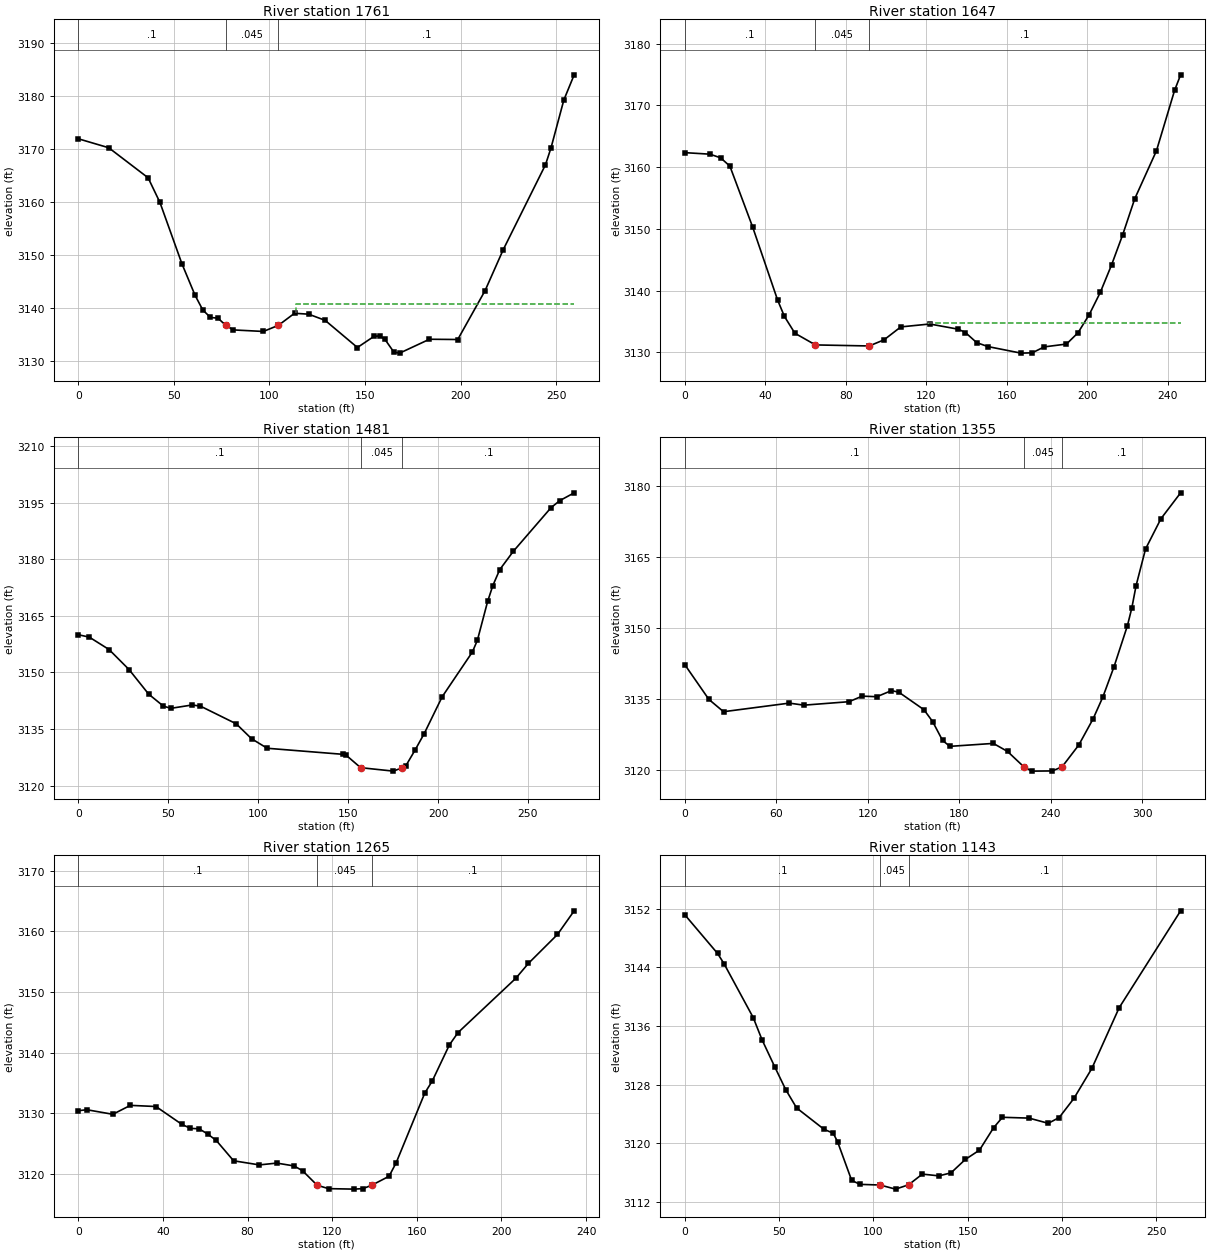
Type RM Length L Ch R = 1 ,1761    ,128,114.5,96.7
XS GIS Cut Line= 4
2192057.82749842511405.779083219 2192071.9280511511462.181293938
2192073.10309716511544.4345179042192137.73063027 511644.31343272
#Sta/Elev= 30
       0 3171.92    15.9 3170.23    36.5 3164.56    42.7  3159.9    54.2 3148.33
    61.1 3142.36    65.1 3139.62    69.1 3138.21    73.1 3138.06    77.1 3136.72
    81.1 3135.85    96.8 3135.56   104.7 3136.72   113.1 3138.99   120.5 3138.82
   129.1 3137.66     146 3132.53   154.7 3134.64   157.6 3134.71   160.3 3134.12
   165.1 3131.65   168.1 3131.47   183.7 3134.09   198.5 3134.04   212.8 3143.27
   222.3    3151   244.4 3167.02   247.3 3170.22     254 3179.24   259.4 3183.99
#Mann= 3 ,-1,0
       0      .1       0    77.1    .045       0   104.7      .1       0
#XS Ineff= 1 ,-1
  114.09 259.364 3140.73
Permanent Ineff=
       F
Bank Sta=77.1,104.7
XS Rating Curve= 0 ,0
Exp/Cntr(USF)=0,0
Exp/Cntr=0.3,0.1

Type RM Length L Ch R = 1 ,1647    ,159.8,166,163.1
XS GIS Cut Line= 4
2191922.69720191511495.0825835242191948.54821515511517.408458601
2192021.40107066511579.6858996042192104.82934069511660.764077513
#Sta/Elev= 30
       0 3162.36    12.5 3162.11    17.8 3161.52    22.4 3160.17    33.7 3150.31
    46.1 3138.47    49.5 3135.81    54.7 3133.09    64.9  3131.2    91.6 3131.03
      99 3132.03   107.3 3134.12   121.7 3134.59   135.8 3133.75   139.4 3133.21
     145 3131.57   150.6 3130.93     167 3129.87   172.6 3129.92   178.5 3130.88
   189.6 3131.34   195.3 3133.16   200.9 3136.11   206.4 3139.72     212 3144.17
   217.5 3149.03   223.5 3154.88   234.3 3162.67   243.3 3172.45   246.3 3174.97
#Mann= 3 ,-1,0
       0      .1       0    64.9    .045       0    91.6      .1       0
#XS Ineff= 2 , 0
                          120.85         3134.69
Permanent Ineff=
       F       F
Bank Sta=64.9,91.6
XS Rating Curve= 0 ,0
Exp/Cntr(USF)=0,0
Exp/Cntr=0.3,0.1

Type RM Length L Ch R = 1 ,1481    ,124.2,125.8,127.5
XS GIS Cut Line= 3
2191893.40436177511555.2320242472191911.60110831511628.683925276
2192033.38323219511787.392788037
#Sta/Elev= 30
       0 3160.02     6.1 3159.39    17.1 3156.09    28.2 3150.78    39.1 3144.26
    47.3 3141.07    51.5 3140.49    63.3 3141.38    67.9 3141.07    87.8 3136.38
    96.3 3132.43     105 3129.89   146.9 3128.29   148.9 3128.05156.97923124.735
   175.2 3123.82180.22923124.753   182.2 3125.31   187.2 3129.38   192.3 3133.76
   202.3 3143.55   219.1 3155.44   221.9 3158.57   227.6 3168.89   230.5 3173.09
   234.3 3177.29   241.9 3182.18   262.8 3193.73   267.6 3195.59   275.7 3197.69
#Mann= 3 ,0,0
       0      .1       0156.9792    .045       0180.2292      .1       0
Bank Sta=156.9792,180.2292
XS Rating Curve= 0 ,0
Exp/Cntr(USF)=0,0
Exp/Cntr=0.3,0.1

Type RM Length L Ch R = 1 ,1355    ,83.6,90.1,95.7
XS GIS Cut Line= 4
2191732.33974073511567.9354390372191838.09388583511728.916748799
2191882.74563598511802.9446503682191910.94674134511839.371078124
#Sta/Elev= 30
       0 3142.26    15.8 3134.94    25.4 3132.35    68.5 3134.16    78.1 3133.73
   107.7 3134.46   116.3 3135.63   125.9 3135.51   135.5 3136.79   140.3 3136.47
   156.8 3132.77   162.5 3130.27     169  3126.3   173.8 3125.05   202.3 3125.67
   211.6 3123.98  222.383120.714   227.6 3119.83   240.9 3119.87  247.333120.715
   258.3 3125.32   267.7 3130.84   274.1 3135.44   281.4  3141.8   290.2 3150.46
   293.1 3154.21   295.9 3158.92   302.1 3166.64   312.2 3173.02   325.1 3178.47
#Mann= 3 ,-1,0
       0      .1       0  222.38    .045       0  247.33      .1       0
Bank Sta=222.38,247.33
XS Rating Curve= 0 ,0
Exp/Cntr(USF)=0,0
Exp/Cntr=0.3,0.1

Type RM Length L Ch R = 1 ,1265    ,131.2,121.6,114.2
XS GIS Cut Line= 3
2191751.08596554511673.2414890742191786.76866654511849.905756719
2191830.43557035511881.961479766
#Sta/Elev= 30
       0 3130.43       4 3130.59    16.3 3129.84    24.6 3131.31    36.7 3131.12
    48.9 3128.19      53 3127.52    57.1 3127.45    61.1  3126.6    65.2 3125.53
    73.4 3122.18    85.6  3121.5    93.8  3121.8     102 3121.33     106 3120.54
   112.9 3118.15   118.3 3117.59   130.5 3117.51   134.6  3117.6   138.7 3118.15
   146.9 3119.63   150.3 3121.89   163.8 3133.35   167.3 3135.31   175.4 3141.26
   179.5  3143.3   206.8 3152.24   212.8 3154.71   226.5 3159.46   234.4 3163.36
#Mann= 3 ,-1,0
       0      .1       0   112.9    .045       0   138.7      .1       0
Bank Sta=112.9,138.7
XS Rating Curve= 0 ,0
Exp/Cntr(USF)=0,0
Exp/Cntr=0.3,0.1

Type RM Length L Ch R = 1 ,1143    ,108.6,103.6,102.8
XS GIS Cut Line= 3
2191597.13429558 511718.468096832191704.42175813511889.542467503
 2191755.6340639511922.752673004
#Sta/Elev= 30
       0 3151.16    17.4 3145.88    20.8 3144.49    36.3 3137.13      41 3134.09
    47.7 3130.42    53.5 3127.32    59.3 3124.81    73.8  3121.9    78.7 3121.36
      81 3120.22    88.5 3114.93    92.9 3114.38   103.6 3114.29   111.8 3113.73
   118.7 3114.32     126 3115.78   134.8 3115.54   141.2 3115.95   148.8 3117.78
   156.3 3119.05   163.8 3122.11   168.5 3123.53   182.6 3123.42   192.8 3122.71
   198.6  3123.5   206.4 3126.11   215.9 3130.19   230.4 3138.48     263  3151.7
#Mann= 3 ,-1,0
       0      .1       0   103.6    .045       0   118.7      .1       0
Bank Sta=103.6,118.7
XS Rating Curve= 0 ,0
Exp/Cntr(USF)=0,0
Exp/Cntr=0.3,0.1

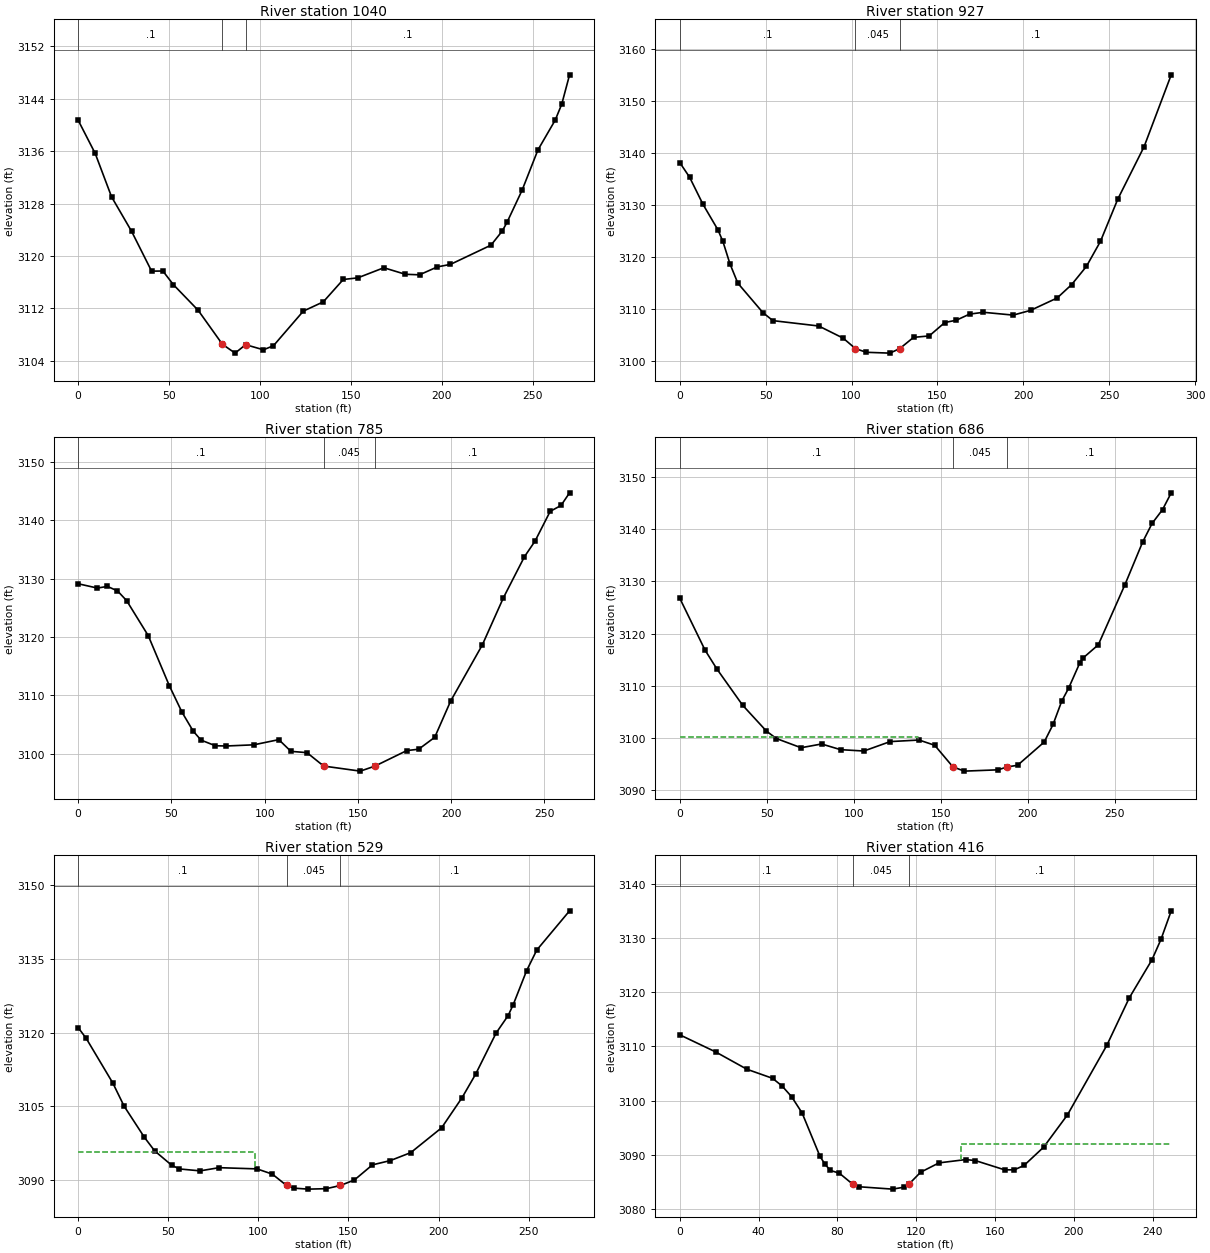
Type RM Length L Ch R = 1 ,1040    ,115.5,112.3,109.1
XS GIS Cut Line= 4
2191506.73089785511805.2947424812191545.50741772511841.721170237
2191619.53531929511920.4492560332191693.56322086512000.352387886
#Sta/Elev= 30
       0 3140.74     9.4 3135.65    18.4 3129.02    29.4 3123.76    40.4 3117.68
    46.6  3117.7    52.4 3115.61      66  3111.7   79.323106.517    86.3 3105.16
    92.1 3106.45   101.9 3105.67   107.4 3106.29   123.8 3111.57   134.8 3112.99
   145.8 3116.41   153.7 3116.65   168.1  3118.2   179.9  3117.2   187.7 3117.12
   197.5 3118.33   204.7 3118.71     227 3121.65   233.2 3123.81   235.8 3125.13
   244.1 3130.04   252.8 3136.19   262.3 3140.74   265.9 3143.18   270.2 3147.66
#Mann= 3 ,-1,0
       0      .1       0   79.32    .045       0    92.1      .1       0
Bank Sta=79.32,92.1
XS Rating Curve= 0 ,0
Exp/Cntr(USF)=0,0
Exp/Cntr=0.3,0.1

Type RM Length L Ch R = 1 ,927     ,139.5,142.2,144.5
XS GIS Cut Line= 4
2191423.30262783 511907.523749412191499.68062151511954.525591676
2191563.13310857511989.7769733762191660.66193127512066.154967058
#Sta/Elev= 30
       0 3138.13     5.7 3135.33    13.5 3130.12    22.2 3125.22    25.1 3122.99
    29.2  3118.7    33.8 3114.97    48.4 3109.32    54.2 3107.78    80.9 3106.75
    95.1 3104.42  102.293102.403   108.6  3101.7   122.3 3101.54  128.053102.405
   136.1 3104.57   145.2 3104.84   154.3 3107.42     161 3107.86   168.7 3109.03
   176.8 3109.38   194.1 3108.84   204.2 3109.75   219.7 3112.13   228.1 3114.69
   236.7 3118.18   244.9    3123     255 3131.12   270.3 3141.18   286.1 3154.98
#Mann= 3 ,-1,0
       0      .1       0  102.29    .045       0  128.05      .1       0
Bank Sta=102.29,128.05
XS Rating Curve= 0 ,0
Exp/Cntr(USF)=0,0
Exp/Cntr=0.3,0.1

Type RM Length L Ch R = 1 ,785     ,98.4,99.2,98.9
XS GIS Cut Line= 4
2191344.57454203511995.6522036592191423.30262783512067.330013115
  2191489.105207512116.6819474942191543.15732561512168.383973987
#Sta/Elev= 30
       0 3129.11    10.3 3128.37    15.7 3128.65    21.1 3127.89      26 3126.22
    37.6 3120.21    48.9 3111.63    55.7 3107.08    61.7 3103.84    65.9  3102.3
    73.6 3101.33    79.5 3101.29    94.2 3101.49   107.6 3102.38   114.1 3100.37
   122.7 3100.15  131.663097.848   151.3 3096.98   159.23097.848   176.2  3100.5
   182.6 3100.74   191.2 3102.78   199.7 3108.97   216.7 3118.61     228 3126.69
   239.3 3133.74     245 3136.43   253.1 3141.52   258.9 3142.53   263.5  3144.7
#Mann= 3 ,-1,0
       0      .1       0  131.66    .045       0   159.2      .1       0
Bank Sta=131.66,159.2
XS Rating Curve= 0 ,0
Exp/Cntr(USF)=0,0
Exp/Cntr=0.3,0.1

Type RM Length L Ch R = 1 ,686     ,157.1,156.4,157.8
XS GIS Cut Line= 4
2191252.92094961512054.4045064922191359.85014077512141.357914684
2191430.35290417512196.5850793472191472.65456221512231.836461047
#Sta/Elev= 30
       0 3126.79    14.5 3116.84    21.3 3113.22    36.1 3106.26    49.8 3101.28
    55.5 3099.86    69.7 3098.09    81.5 3098.81    92.4 3097.72   105.8 3097.46
   120.9 3099.27   137.5 3099.57   146.5 3098.56  156.953094.419   163.5  3093.6
   182.9 3093.85  188.27 3094.42   194.1 3094.72   209.4 3099.18   214.5 3102.56
   219.5 3107.05   223.4 3109.49   229.8 3114.32   231.9 3115.36   240.5 3117.85
   255.8 3129.39     266 3137.59   271.4 3141.15   277.4 3143.79   282.4 3147.02
#Mann= 3 ,-1,0
       0      .1       0  156.95    .045       0  188.27      .1       0
#XS Ineff= 2 , 0
          136.96 3100.09
Permanent Ineff=
       F       F
Bank Sta=156.95,188.27
XS Rating Curve= 0 ,0
Exp/Cntr(USF)=0,0
Exp/Cntr=0.3,0.1

Type RM Length L Ch R = 1 ,529     ,114.4,113.4,112.5
XS GIS Cut Line= 4
2191164.79249536512176.6092963842191238.82039693512240.061783443
2191332.82408146512315.2647310692191371.60060133512354.041250938
#Sta/Elev= 30
       0 3121.07     4.5 3118.86    19.3 3109.74    25.5 3105.07    36.8  3098.7
    42.5 3095.94    51.9 3093.03    56.2 3092.27    67.7 3091.88    78.2 3092.53
    99.3 3092.28   107.8 3091.21  115.663088.899   119.7 3088.36   127.7 3088.16
   137.7 3088.25  145.51  3088.9   153.3 3090.02   163.3  3093.1   173.3 3093.98
   184.6  3095.6   201.7 3100.65   213.1 3106.82   220.6 3111.59   231.9 3119.93
   238.6  3123.5   241.4  3125.7   248.9 3132.68   254.5 3136.85   272.7 3144.84
#Mann= 3 ,-1,0
       0      .1       0  115.66    .045       0  145.51      .1       0
#XS Ineff= 2 , 0
           98.02  3095.8
Permanent Ineff=
       F       F
Bank Sta=115.66,145.51
XS Rating Curve= 0 ,0
Exp/Cntr(USF)=0,0
Exp/Cntr=0.3,0.1

Type RM Length L Ch R = 1 ,416     ,66.5,61.8,58.3
XS GIS Cut Line= 4
2191113.09046887512294.1139020492191174.19286382512335.240514032
 2191258.7961799512396.3429089782191316.37343667512438.644567018
#Sta/Elev= 30
       0 3112.13    18.2 3108.98    34.1 3105.78    47.1 3104.11    51.9 3102.71
    56.8 3100.71    62.1 3097.72    71.2 3089.71    73.8 3088.23    76.5 3087.12
      81 3086.62   87.893084.562    90.9 3084.12     108 3083.68   113.7 3084.03
  116.233084.563   122.3  3086.8   131.6 3088.52   145.2 3089.13   150.1 3088.94
   164.9 3087.24   169.8 3087.23   174.8 3088.05   184.7 3091.41   196.8 3097.36
   216.8 3110.19   228.2 3118.94   239.7 3125.95   244.3 3129.73   249.5 3134.99
#Mann= 3 ,-1,0
       0      .1       0   87.89    .045       0  116.23      .1       0
#XS Ineff= 1 ,-1
  142.74249.4612    3092
Permanent Ineff=
       T
Bank Sta=87.89,116.23
XS Rating Curve= 0 ,0
Exp/Cntr(USF)=0,0
Exp/Cntr=0.3,0.1

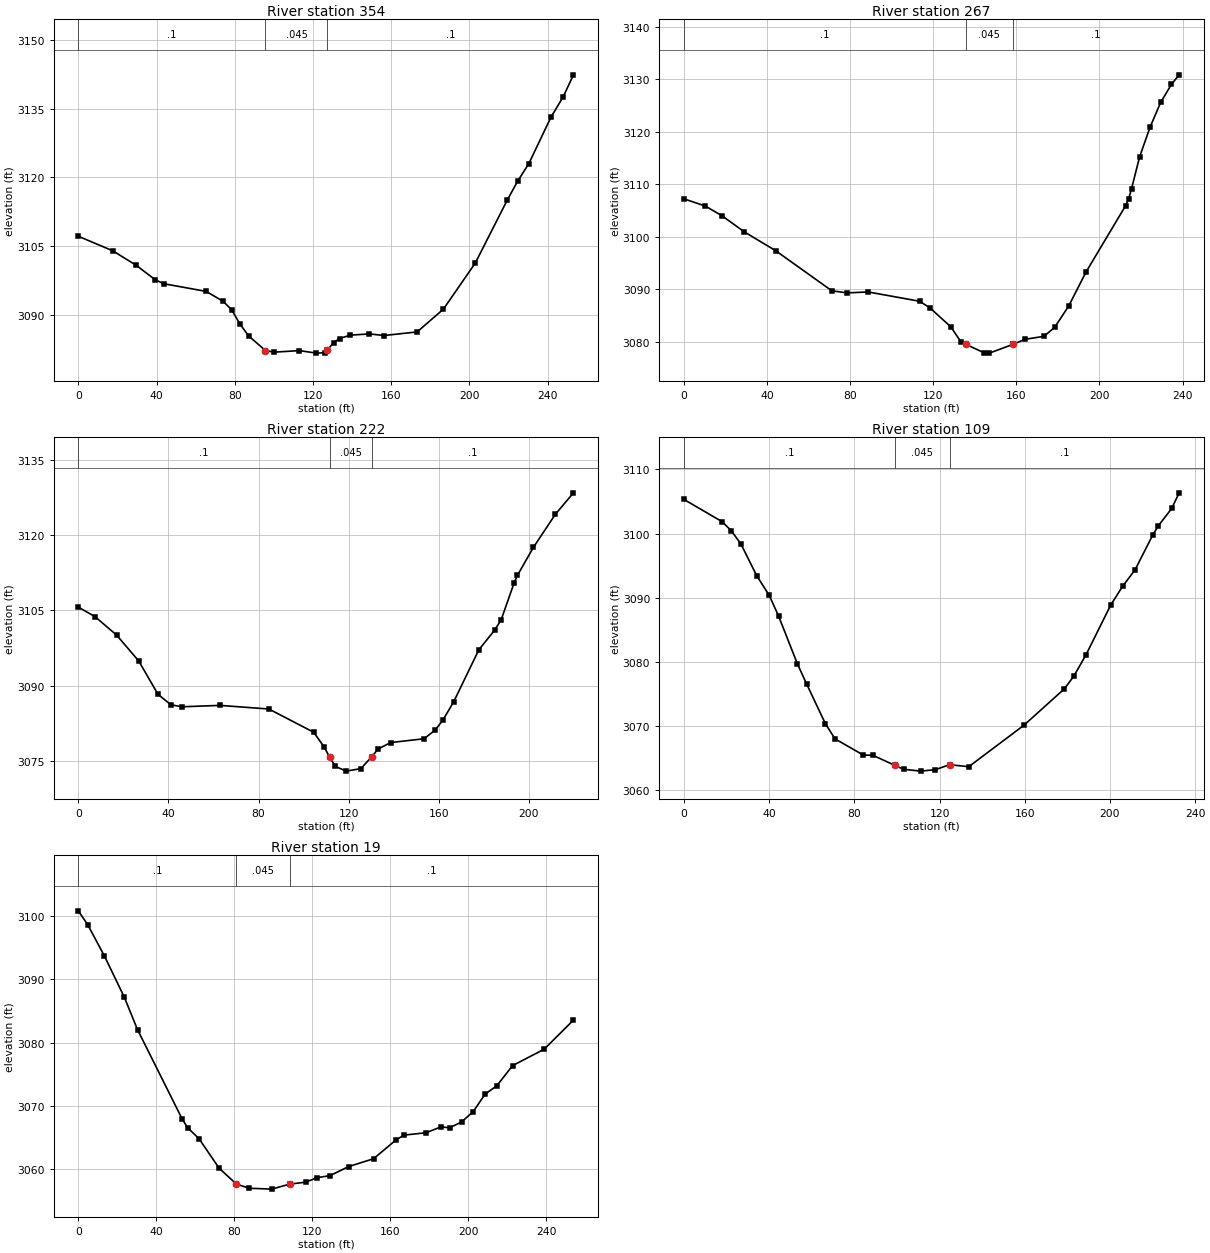
Type RM Length L Ch R = 1 ,354     ,78.1,87.6,92.9
XS GIS Cut Line= 3
2191071.82831558 512366.836868922191237.51656271512435.952537722
2191287.69643184512489.919566787
#Sta/Elev= 30
       0 3107.11    17.7 3103.91    29.6 3100.76    39.4 3097.58    43.7 3096.73
    65.4 3095.05    74.1 3092.87    78.4 3091.04    82.7  3087.9    87.1 3085.32
    95.7 3082.13   100.1 3081.77   113.1 3082.11   121.7 3081.56   126.1 3081.65
   127.4 3082.25   130.5 3083.84   133.6 3084.75   139.1 3085.49   148.9 3085.76
   156.4 3085.41   173.3  3086.2   186.7 3091.17     203 3101.25   219.4 3115.05
   224.7 3119.17   230.4    3123   241.7 3133.13     248 3137.62   253.2 3142.39
#Mann= 3 ,-1,0
       0      .1       0    95.7    .045       0   127.4      .1       0
Bank Sta=95.7,127.4
XS Rating Curve= 0 ,0
Exp/Cntr(USF)=0,0
Exp/Cntr=0.3,0.1

Type RM Length L Ch R = 1 ,267     ,44.5,44.9,45
XS GIS Cut Line= 4
2191066.11993241512369.6863019922191131.65048842512459.116237253
2191174.82356062512516.9373160862191209.51620792512560.110388282
#Sta/Elev= 30
       0 3107.22    10.2 3105.86    18.3    3104    29.1 3100.92    44.1 3097.36
    71.2 3089.71    78.7 3089.32    88.6  3089.5   113.4 3087.73   118.4 3086.47
   128.4 3082.87   133.4 3079.96   135.6 3079.55   144.2 3077.96     147 3077.85
   158.4 3079.52   158.4 3079.53   164.2 3080.48   173.3 3081.05   178.5 3082.78
   185.2 3086.82   193.6 3093.33   212.6 3105.91   214.1 3107.28   215.5 3109.19
   219.3 3115.16   224.4 3120.89   229.5 3125.61   234.7 3129.04   238.4 3130.84
#Mann= 3 ,-1,0
       0      .1       0   135.6    .045       0   158.4      .1       0
Bank Sta=135.6,158.4
XS Rating Curve= 0 ,0
Exp/Cntr(USF)=0,0
Exp/Cntr=0.3,0.1

Type RM Length L Ch R = 1 ,222     ,110.5,113.1,114.1
XS GIS Cut Line= 4
2191049.16245577512415.0736062212191096.27592741512485.315509395
2191140.81957333512546.9913268172191174.22730777512595.818015609
#Sta/Elev= 30
       0 3105.61     7.4 3103.72      17 3100.04    26.8  3094.9    35.4 3088.23
    41.1 3086.17    45.9 3085.76    62.9 3086.04    84.6 3085.32   104.5 3080.69
   109.1 3077.78  111.593075.747     114 3073.91   118.9 3072.95   125.4 3073.44
   130.2 3075.78   133.1 3077.37   138.7 3078.64   153.5  3079.4   158.4 3081.12
   161.8 3083.08   166.6 3086.73   177.8 3097.11   184.8 3101.02   187.7 3103.07
   193.4 3110.36   194.9 3111.91     202 3117.49   211.8 3124.11   219.8 3128.37
#Mann= 3 ,-1,0
       0      .1       0  111.59    .045       0   130.2      .1       0
Bank Sta=111.59,130.2
XS Rating Curve= 0 ,0
Exp/Cntr(USF)=0,0
Exp/Cntr=0.3,0.1

Type RM Length L Ch R = 1 ,109     ,93.3,90,90
XS GIS Cut Line= 4
2190970.90989602512460.970442094 2191003.8111856512531.473205493
2191051.98807392512625.4768900262191087.23945562512659.553225669
#Sta/Elev= 30
       0 3105.31    17.9 3101.85    22.2 3100.44    26.7 3098.38    34.2 3093.39
      40 3090.38    44.4 3087.14    53.2 3079.72    57.6 3076.53    66.4 3070.35
    70.9    3068    84.2 3065.47    88.7 3065.44   98.863063.887   103.1 3063.26
   111.2 3062.97     118  3063.2   124.7 3063.97   133.7 3063.66   159.6 3070.12
   178.6  3075.8   183.1 3077.81   188.8 3081.13   200.3 3088.82   205.9 3091.76
   211.8 3094.36   220.1 3099.78   222.6 3101.16     229 3103.92   232.5 3106.35
#Mann= 3 ,-1,0
       0      .1       0   98.86    .045       0   124.7      .1       0
Bank Sta=98.86,124.7
XS Rating Curve= 0 ,0
Exp/Cntr(USF)=0,0
Exp/Cntr=0.3,0.1

Type RM Length L Ch R = 1 ,19      ,,,
XS GIS Cut Line= 4
2190873.38107331512509.1473304172190919.20786952512565.549541136
2190974.43503419512652.5029493292191026.13706068512711.255252161
#Sta/Elev= 30
       0 3100.87     4.9 3098.64    13.4 3093.71    23.5 3087.26    30.4 3082.03
    53.2 3067.94      56 3066.54    61.9 3064.79    72.2 3060.12   81.04  3057.6
    87.6 3056.94    99.2  3056.8  108.42  3057.6   116.6  3057.9   122.4 3058.61
   129.1 3058.94   138.6 3060.37   151.4 3061.61   162.9 3064.59     167 3065.35
   178.3 3065.73   185.9 3066.65   190.4 3066.52   196.5 3067.43   202.5 3069.07
   208.6 3071.85   214.6 3073.17   222.7 3076.36   238.9 3078.96   253.9 3083.57
#Mann= 3 ,-1,0
       0      .1       0   81.04    .045       0  108.42      .1       0
Bank Sta=81.04,108.42
XS Rating Curve= 0 ,0
Exp/Cntr(USF)=0,0
Exp/Cntr=0.3,0.1
LCMann Table=0

Chan Stop Cuts=-1
Use User Specified Reach Order=0
Composite Channel Slope=5